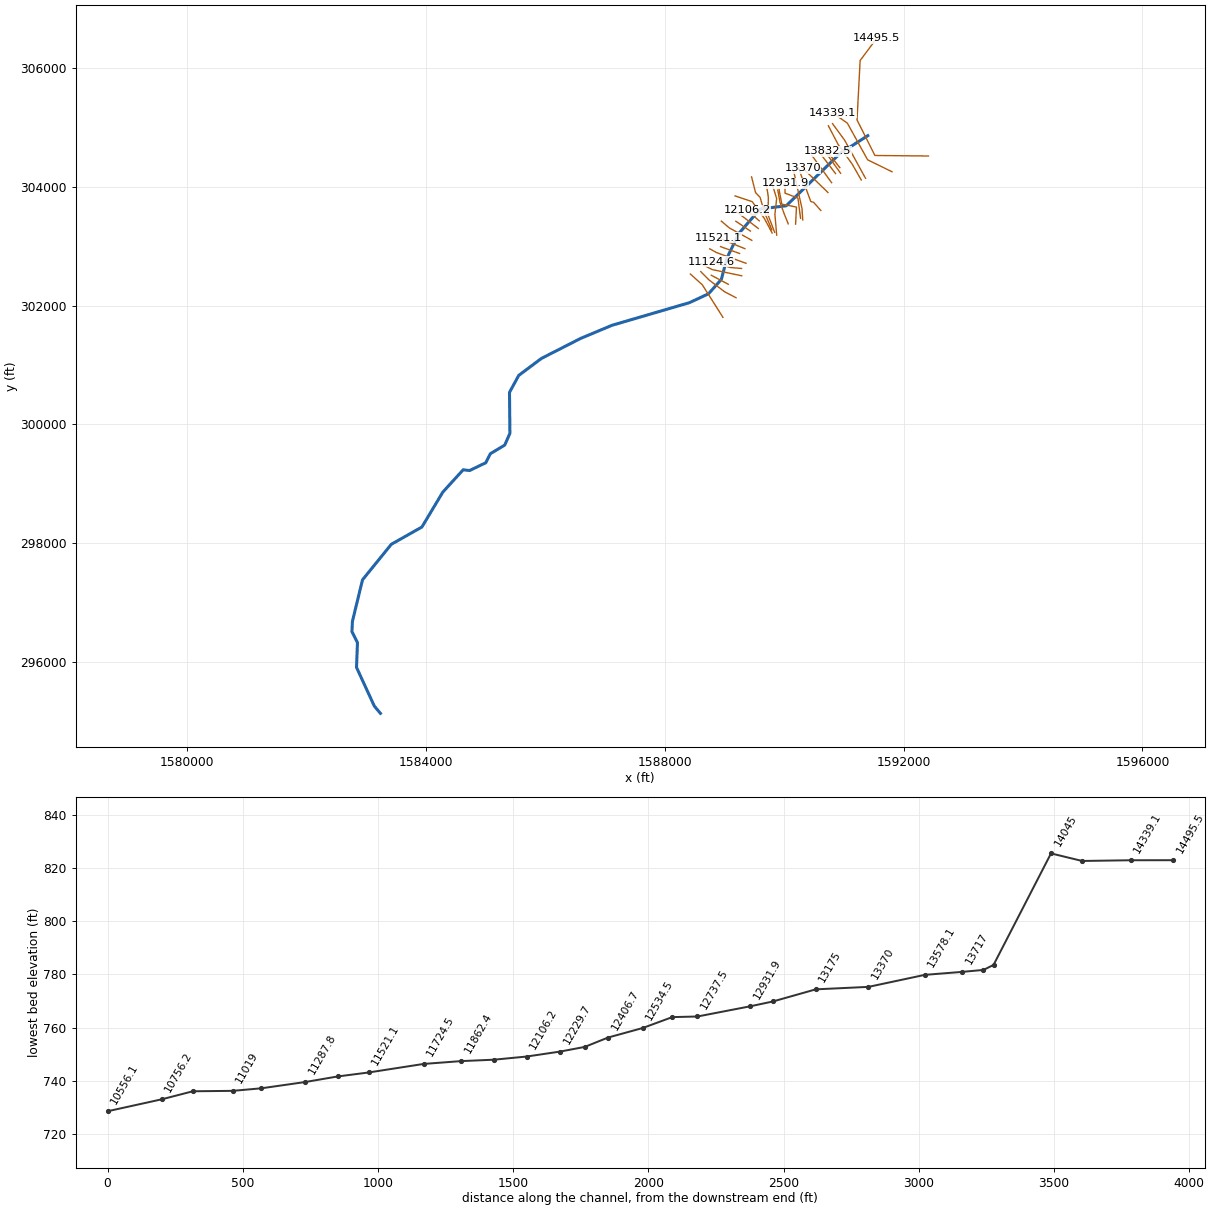
--- bgbrnch.prj (project) ---

Proj Title=bgbrnch
Current Plan=p01
Default Exp/Contr=0,0
English Units
Geom File=g01
Flow File=f01
Plan File=p01
BEGIN DESCRIPTION:
END DESCRIPTION:
DSS Export Rating Curves= 0
DSS Export Rating Curve Sorted= 0
DSS Export Volume Flow Curves= 0
DXF OffsetX= 0
DXF OffsetY= 0
DXF ScaleX= 0
DXF ScaleY= 0

--- bgbrnch.p01 (plan) ---

Plan Title=Approximate Study - 100yr
Program Version=4.00
Geom File=g01
Flow File=f01
Subcritical Flow
K Sum by GR= 0
Std Step Tol= 0.01
Critical Tol= 0.01
Num of Std Step Trials= 20
Max Error Tol= 0.3
Flow Tol Ratio= 0.001
Split Flow NTrial= 30
Split Flow Tol= 0.02
Split Flow Ratio= 0.02
Log Output Level= 0
Friction Slope Method= 1
Unsteady Friction Slope Method= 2
Unsteady Bridges Friction Slope Method= 1
Parabolic Critical Depth
Global Vel Dist= 0 , 0 , 0
Global Log Level= 0
CheckData=True
Encroach Param=-1 ,0,0, 0
Run HTab= 0
Run UNet= 0
Run PostProcess= 0
Run WQNet= 0
UNET Theta= 0
UNET Theta Warmup= 0
UNET ZTol= 0
UNET ZSATol= 0
UNET MxIter= 0
UNET MaxInSteps= 0
UNET DtIC= 0
UNET DtMin= 0
UNET MaxCRTS= 0
UNET WFStab= 0
UNET SFStab= 0
UNET WFX= 1
UNET SFX= 1
UNET DSS MLevel= 1
UNET DZMax Abort= 0
UNET Convert EG Bridges= 0
UNET Use Existing IB Tables= 0
UNET Froude Reduction=False
UNET Froude Limit= 0
UNET Froude Power= 0
UNET Time Slicing=0,0, 5
Write IC File= 0
Echo Input=False
Echo Output=False
Write Detailed= 0
Detailed Automatic Start=False, 0
WQ ULTIMATE=-1
WQ Max Comp Step=1HOUR
WQ Output Interval=15MIN
WQ Output Selected Increments= 0
WQ Output face flow=0
WQ Output face velocity=0
WQ Output face area=0
WQ Output face dispersion=0
WQ Output cell volume=0
WQ Output cell surface area=0
WQ Output cell continuity=0
WQ Output face conc=0
WQ Output face dconc_dx=0
WQ Output face courant=0
WQ Output face peclet=0
WQ Output face adv mass=0
WQ Output face disp mass=0
WQ Output cell mass=0
WQ Output cell source sink temp=0
WQ Output cell source sink nsm=0
WQ Output MaxMinRange=-1
WQ Daily Max Min Mean=-1
WQ Daily Range=0
WQ Daily Time=0
WQ Create Restart=0
WQ Fixed Restart=0
WQ System Summary=False
Sorting and Armoring Iterations= 10
XS Update Threshold= 0.02
Hydraulics Update Threshold= 0.02
Energy Slope Method= 1
Volume Change Method= 0
XS Weighting Method= 0
Number of US Weighted Cross Sections= 1
Number of DS Weighted Cross Sections= 1
Upstream XS Weight=0.25
Main XS Weight=0.5
Downstream XS Weight=0.25
Number of DS XS's Weighted with US Boundary= 1
Upstream Boundary Weight= 1
Weight of XSs Associated with US Boundary= 0
Number of US XS's Weighted with DS Boundary= 1
Downstream Boundary Weight= 0.5
Weight of XSs Associated with DS Boundary= 0.5
Sediment Output Level= 4
Mass or Volume Output= 0
Output Increment Type= 1
Profile and TS Output Increment= 10
XS Output Flag= 0
XS Output Increment= 10
Disregard all LS=0
Disregard all Conn=0
Disregard all Breaches=0
Disregard all Pumps=0

--- bgbrnch.f01 (steady flow) ---

Flow Title=USGS Regression Equation
Program Version=4.00
Number of Profiles= 1
Profile Names=P100yr
River Rch & RM=bgbrnch,Main            ,14495.5
     295
River Rch & RM=bgbrnch,Main            ,14339.1
     366
River Rch & RM=bgbrnch,Main            ,13832.5
     376
River Rch & RM=bgbrnch,Main            ,12534.5
     410
River Rch & RM=bgbrnch,Main            ,11985.5
     455
River Rch & RM=bgbrnch,Main            ,10756.2
     477
River Rch & RM=bgbrnch,Main            ,10410.1
     640
River Rch & RM=bgbrnch,Main            ,8793.7
     657
River Rch & RM=bgbrnch,Main            ,8303.4
     886
River Rch & RM=bgbrnch,Main            ,6942.5
     925
River Rch & RM=bgbrnch,Main            ,2957.3
    1000
River Rch & RM=bgbrnch,Main            ,2679.3
    1217
Boundary for River Rch & Prof#=bgbrnch,Main            , 1
Up Type= 0
Dn Type= 3
Dn Slope=0.01196
DSS Import GetInterval= 0
DSS Import GetPeak= 0
DSS Import FillOption= 0

--- bgbrnch.g01 (geometry) ---

Geom Title=USGS 3m DEM
Program Version=4.00

River Reach=bgbrnch         ,Main
Reach XY= 30
     1591400.132      304855.581       1590938.1      304559.936
      1590033.94      303676.866     1589596.981      303622.793
      1589240.29      303212.228     1589040.462      302796.697
     1588947.201      302438.445     1588732.202      302197.078
     1588411.866      302047.176     1587115.809      301667.179
      1586591.16      301446.834     1585933.549      301110.019
     1585553.758      300824.249      1585399.12      300539.534
     1585405.871      299850.508     1585318.668       299652.25
     1585078.229      299508.139     1585001.665      299356.296
     1584730.657      299225.039     1584624.007      299238.588
     1584282.799      298863.273      1583931.99      298275.531
     1583419.948      297985.342     1582937.273      297387.665
     1582768.725      296692.066     1582760.207      296517.713
     1582852.905      296332.133     1582836.929       295915.77
     1583134.758      295265.407     1583237.303      295142.317

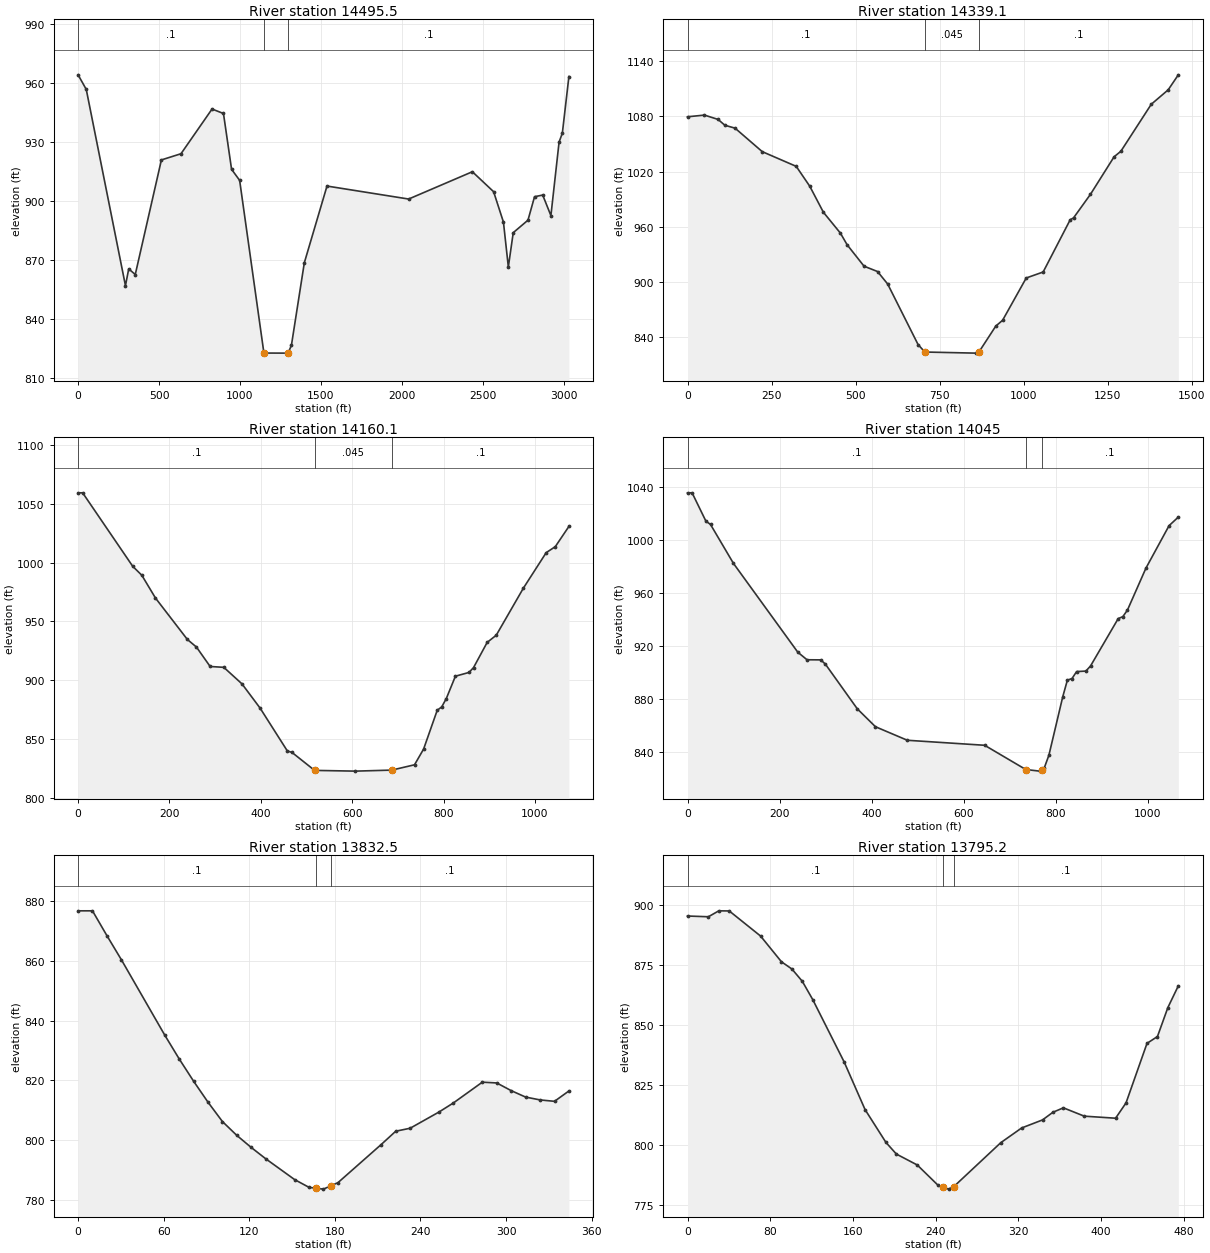
Type RM Length L Ch R = 1 ,14495.5 ,155.6,156.4,157.2
XS GIS Cut Line= 5
     1592416.877      304513.811     1591518.874      304522.488
      1591219.54      305121.156     1591271.598      306118.937
     1591549.241      306492.021
#Sta/Elev= 30
       0  964.37    50.5  956.96   292.6  857.19   312.8  865.71   353.2  862.85
   514.6   921.1   635.7  924.26   827.4  946.98     898  944.71     948  916.35
   997.9  910.71  1147.8  822.92  1287.7  822.88  1297.6     823  1317.6  826.81
  1397.5  868.85  1537.4  907.82  2041.7  901.22  2435.3   915.1  2566.5  904.95
  2627.2  889.52  2657.5  866.69  2687.8  884.13  2778.8  890.48  2819.3   902.4
  2869.8  903.24  2920.4   892.8  2970.9  930.16  2991.1  934.72  3031.6   963.5
#Mann= 3 , 0 , 0
       0      .1       0  1147.8    .045       0  1297.6      .1       0
Bank Sta=1147.8,1297.6
XS Rating Curve= 0 ,0
Exp/Cntr=0.3,0.1

Type RM Length L Ch R = 1 ,14339.1 ,179.1,179,178.9
XS GIS Cut Line= 4
     1591805.194      304249.182     1591396.959      304449.818
     1591057.286      305066.312     1590809.887      305238.823
#Sta/Elev= 30
       0 1079.45    50.5 1081.26      91 1076.57   111.2 1070.23   141.5 1067.09
   222.4 1041.59   323.5 1025.62   363.9 1003.97   404.3  975.81   454.9  953.16
     475  940.46   525.3  917.24   565.5  911.43   595.6  897.88   686.1  832.12
   706.3  824.05   857.1  822.86   867.1  824.08   917.4  852.28   937.5   858.5
  1007.9  904.45  1058.2  910.93  1138.6  967.59  1148.7  969.72    1199  995.29
  1269.3 1036.02  1289.4 1041.99  1379.9 1093.03  1430.2 1108.69  1460.4 1124.99
#Mann= 3 , 0 , 0
       0      .1       0   706.3    .045       0   867.1      .1       0
Bank Sta=706.3,867.1
XS Rating Curve= 0 ,0
Exp/Cntr=0.3,0.1

Type RM Length L Ch R = 1 ,14160.1 ,112.7,115.1,117.5
XS GIS Cut Line= 4
     1591361.454      304139.282     1591203.955      304427.944
     1591013.546      304776.926     1590808.743      305058.027
#Sta/Elev= 30
       0 1059.33      10 1059.33   119.6  996.82   139.5   989.2   169.4  969.82
   239.2  934.58   259.1  928.11     289   911.6   318.9  910.89   358.7  896.81
   398.4  876.17     458  839.74     468  838.55   517.7  823.21   607.1  822.59
   686.6  823.46   736.3  827.98   756.2  841.36     786  874.36   795.9  877.26
   805.9  884.35   825.8  903.34   855.6  906.55   865.5  910.67   895.3  932.09
   915.2  938.21   974.8   978.4  1024.5 1008.44  1044.4 1013.54  1074.2 1030.74
#Mann= 3 , 0 , 0
       0      .1       0   517.7    .045       0   686.6      .1       0
Bank Sta=517.7,686.6
XS Rating Curve= 0 ,0
Exp/Cntr=0.3,0.1

Type RM Length L Ch R = 1 ,14045   ,211.7,212.5,213.4
XS GIS Cut Line= 4
     1591290.371      304110.406     1591137.106      304379.527
     1590901.742      304709.839      1590739.49       305021.83
#Sta/Elev= 30
       0  1035.5      10  1035.5      40 1014.12      50 1011.63    99.9  982.23
   239.8  915.19   259.8  909.49   289.7  909.41   299.7  906.21   369.1  872.46
   408.6  858.94   477.9  848.72     646  844.94   735.4  826.64   765.5  825.43
  769.95  826.49   775.6  827.88   785.6  837.39   815.8  881.62   825.8   894.1
   835.9  895.34   845.9  900.58     866  900.94   876.1  904.77   936.3  940.57
   946.4  942.05   956.4  947.01   996.6  978.67  1046.9 1010.74    1067 1017.19
#Mann= 3 , 0 , 0
       0      .1       0   735.4    .045       0  769.95      .1       0
Bank Sta=735.4,769.95
XS Rating Curve= 0 ,0
Exp/Cntr=0.3,0.1

Type RM Length L Ch R = 1 ,13832.5 ,38,37.2,36.5
XS GIS Cut Line= 2
     1590931.237      304317.651     1590720.196      304589.431
#Sta/Elev= 30
       0  876.81    10.1  876.81    20.2   868.5    30.4  860.38    60.7   835.2
    70.8  827.24      81  819.69    91.1  812.66   101.2  806.18   111.3  801.53
   121.4  797.49   131.6  793.69   151.8  786.73   161.9  784.13   166.9  783.83
     172  783.53   177.2  784.64   182.2   785.7   212.5  798.48   222.7  802.94
   232.8  803.94     253  809.37   263.1  812.41   283.4  819.38   293.5  819.12
   303.6  816.55   313.7  814.39   323.9  813.43     334  812.96   344.1  816.43
#Mann= 3 , 0 , 0
       0      .1       0   166.9    .045       0   177.2      .1       0
Bank Sta=166.9,177.2
XS Rating Curve= 0 ,0
Exp/Cntr=0.3,0.1

Type RM Length L Ch R = 1 ,13795.2 ,77.7,78.2,78.8
XS GIS Cut Line= 2
     1590944.819       304223.59     1590668.464      304609.756
#Sta/Elev= 30
       0  895.34    20.2  895.03    30.3   897.5    40.4  897.45    70.7     887
    90.9  876.29     101  873.29   111.1  868.15   121.2  860.53   151.6  834.56
   171.8  814.76     192   801.1   202.1  796.25   222.3   791.7   242.5  783.22
   247.5  782.44   252.6  781.65   257.7  782.71   303.1  800.98   323.3  807.11
   343.5  810.46   353.6  813.66   363.7  815.49   383.9  812.02   414.2  811.17
   424.3  817.55   444.6  842.34   454.7  845.17   464.8  857.25   474.9  866.28
#Mann= 3 , 0 , 0
       0      .1       0   247.5    .045       0   257.7      .1       0
Bank Sta=247.5,257.7
XS Rating Curve= 0 ,0
Exp/Cntr=0.3,0.1

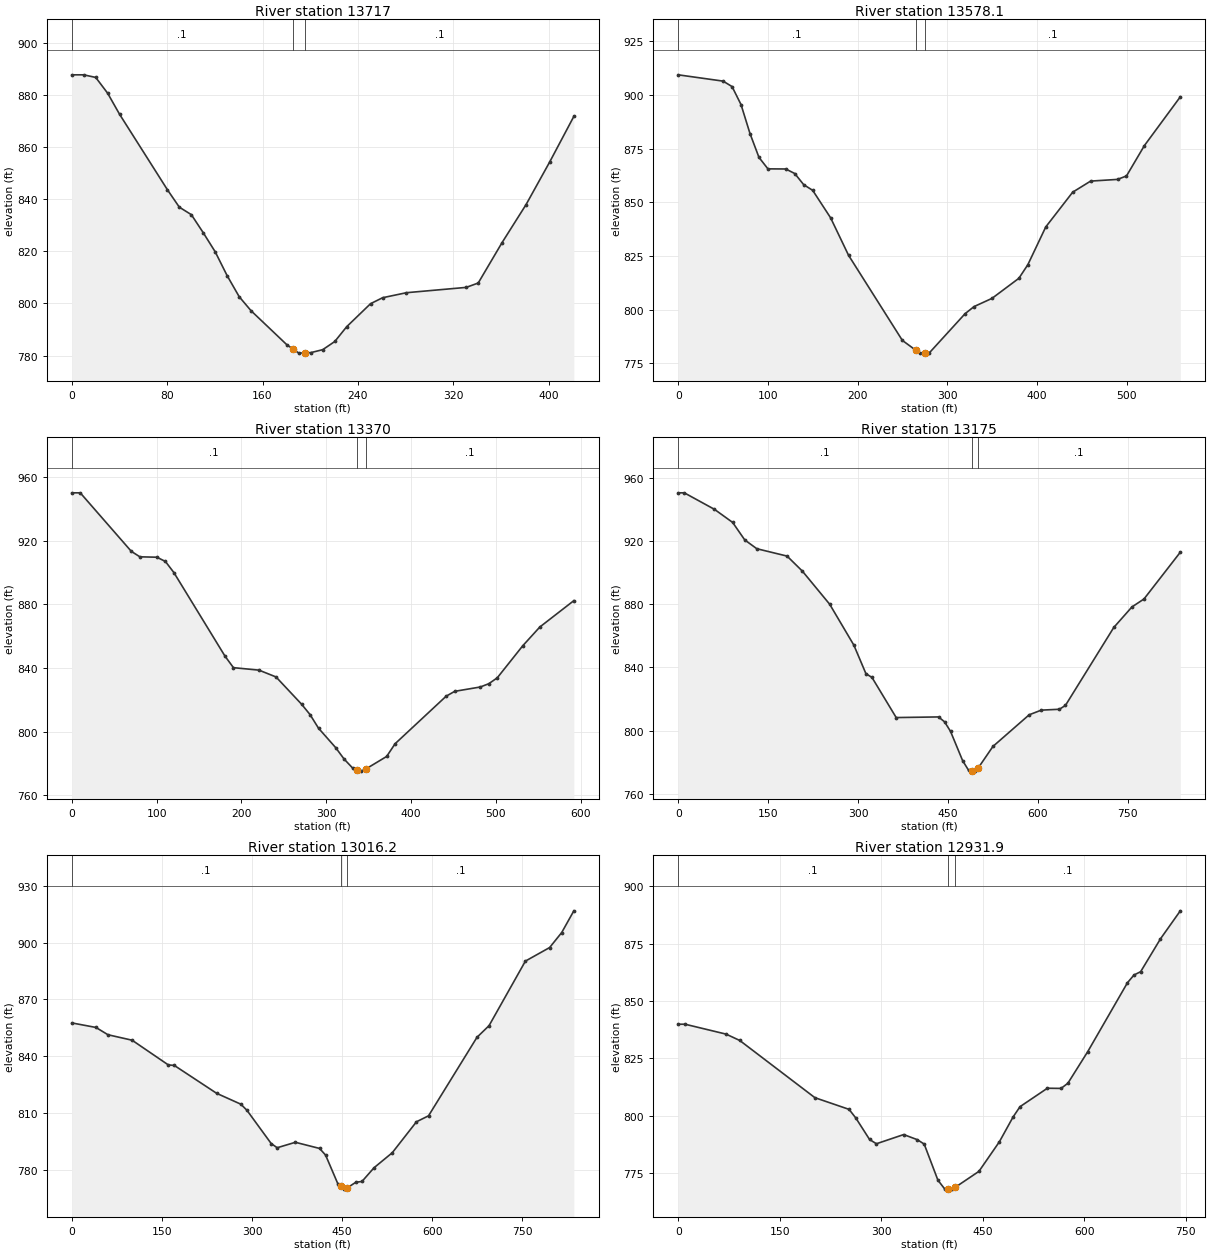
Type RM Length L Ch R = 1 ,13717   ,139.3,138.9,138.4
XS GIS Cut Line= 2
     1590859.232       304218.48     1590604.953      304554.087
#Sta/Elev= 30
       0  887.82      10  887.82    20.1  886.82    30.1  880.75    40.1  872.66
    80.2  843.69    90.2  836.99   100.3   834.1   110.3  827.15   120.3  819.84
   130.3  810.69   140.4  802.61   150.4  797.19   180.5  784.09   185.3  782.57
   190.5  780.92   195.6  781.01   200.5  781.11   210.5  782.25   220.6  785.39
   230.6  791.08   250.6  799.91   260.7   802.2   280.7  804.13   330.8  806.17
   340.9  807.85   360.9  823.38     381  837.96     401  854.48   421.1  871.85
#Mann= 3 , 0 , 0
       0      .1       0   185.3    .045       0   195.6      .1       0
Bank Sta=185.3,195.6
XS Rating Curve= 0 ,0
Exp/Cntr=0.3,0.1

Type RM Length L Ch R = 1 ,13578.1 ,204.7,208.2,211.7
XS GIS Cut Line= 2
     1590794.288      304064.708     1590466.688       304518.59
#Sta/Elev= 30
       0  909.34      50  906.41      60  903.87      70   895.5      80  882.02
      90  870.92     100  865.57   119.9  865.51   129.9   863.4   139.9   858.2
   149.9  855.57   169.9  842.77   189.9  825.33   249.9  785.71   264.7  781.18
   269.9  779.79     275  779.84   279.9  779.88   319.9  798.18   329.9  801.47
   349.8  805.27   379.8  814.62   389.8  820.95   409.8  838.54   439.8  854.71
   459.8  859.87   489.8  860.66   499.8  862.27   519.8  876.43   559.8   899.1
#Mann= 3 , 0 , 0
       0      .1       0   264.7    .045       0     275      .1       0
Bank Sta=264.7,275
XS Rating Curve= 0 ,0
Exp/Cntr=0.3,0.1

Type RM Length L Ch R = 1 ,13370   ,204.5,194.9,185.3
XS GIS Cut Line= 2
     1590732.475      303900.241     1590307.875       304312.64
#Sta/Elev= 30
       0  950.07      10  950.07    70.2  913.32    80.3  909.88   100.3  909.63
   110.4  906.97   120.4  899.97   180.6  847.53   190.6  840.26   220.7  838.71
   240.8  834.43   270.9  817.32   280.9  810.79   290.9  802.23     311  790.11
     321   782.9   331.1  777.21   335.9  776.29   341.1  775.28   346.3   776.5
   371.2  784.49   381.2   792.5   441.4  822.36   451.5   825.4   481.6  828.12
   491.6  830.18   501.6  833.87   531.7  854.03   551.8   865.8   591.9  882.35
#Mann= 3 , 0 , 0
       0      .1       0   335.9    .045       0   346.3      .1       0
Bank Sta=335.9,346.3
XS Rating Curve= 0 ,0
Exp/Cntr=0.3,0.1

Type RM Length L Ch R = 1 ,13175   ,162.2,158.8,155.4
XS GIS Cut Line= 4
     1590612.903      303597.654     1590493.333      303734.306
     1590444.528      303748.948     1590237.109       304317.52
#Sta/Elev= 30
       0  950.32    10.1  950.32    60.5  939.87    90.8   931.6     111  920.53
   131.1  914.98   181.6  910.32   207.1  900.83   252.7  879.88   293.1  853.98
   313.2  835.97   323.3  833.58   363.7  808.22   434.3  808.62   444.4  805.53
   454.4  799.46   474.6  780.94   484.7  774.76   489.6  774.56   494.8  774.35
     500  776.04   525.1  789.95   585.6  809.97   605.8  812.91     636  813.47
   646.1  815.89   726.8  865.19   757.1  878.17   777.2   883.2   837.8  912.77
#Mann= 3 , 0 , 0
       0      .1       0   489.6    .045       0     500      .1       0
Bank Sta=489.6,500
XS Rating Curve= 0 ,0
Exp/Cntr=0.3,0.1

Type RM Length L Ch R = 1 ,13016.2 ,62.7,84.3,105.9
XS GIS Cut Line= 3
     1590310.315      303439.039     1590298.114      303629.376
     1590159.022      304258.955
#Sta/Elev= 30
       0  857.56    40.2  855.16    60.2  851.31   100.4  848.42   160.6  835.39
   170.7  835.09   241.1  820.38   281.4  814.63   291.5  811.42   331.8  793.88
   341.8  791.64   372.1  794.52   412.4  791.27   422.4  787.74   442.6  772.74
   447.4  771.33   452.7  769.79   457.9  770.35   472.8  773.44   482.9  773.82
     503  781.08   533.3  788.99   573.6  805.35   593.7  808.51   674.3  849.95
   694.4  856.11   754.9   890.2   795.2  897.35   815.3  905.27   835.5  916.74
#Mann= 3 , 0 , 0
       0      .1       0   447.4    .045       0   457.9      .1       0
Bank Sta=447.4,457.9
XS Rating Curve= 0 ,0
Exp/Cntr=0.3,0.1

Type RM Length L Ch R = 1 ,12931.9 ,189.9,194.4,199.6
XS GIS Cut Line= 4
     1590273.978      303465.423     1590230.054      303805.834
     1590013.179      303889.564     1590015.924      304055.652
#Sta/Elev= 30
       0   839.9    10.1   839.9    70.7  835.58    90.9  832.81   201.9  807.86
   252.4  802.76   262.5  798.94   282.7  789.62   292.8  787.76   333.1  791.77
   353.3  789.53   363.4  787.62   383.7  771.85   393.8  768.01   398.6  767.99
   403.9  767.97   409.2  768.75   444.3  775.73   474.6  788.68   494.8  799.48
     505  803.94   545.4  811.98   565.6   811.9   575.7  814.16     605  827.93
   663.7  857.99   673.4  861.38   683.2  862.81   712.5  877.15   741.8  889.36
#Mann= 3 , 0 , 0
       0      .1       0   398.6    .045       0   409.2      .1       0
Bank Sta=398.6,409.2
XS Rating Curve= 0 ,0
Exp/Cntr=0.3,0.1

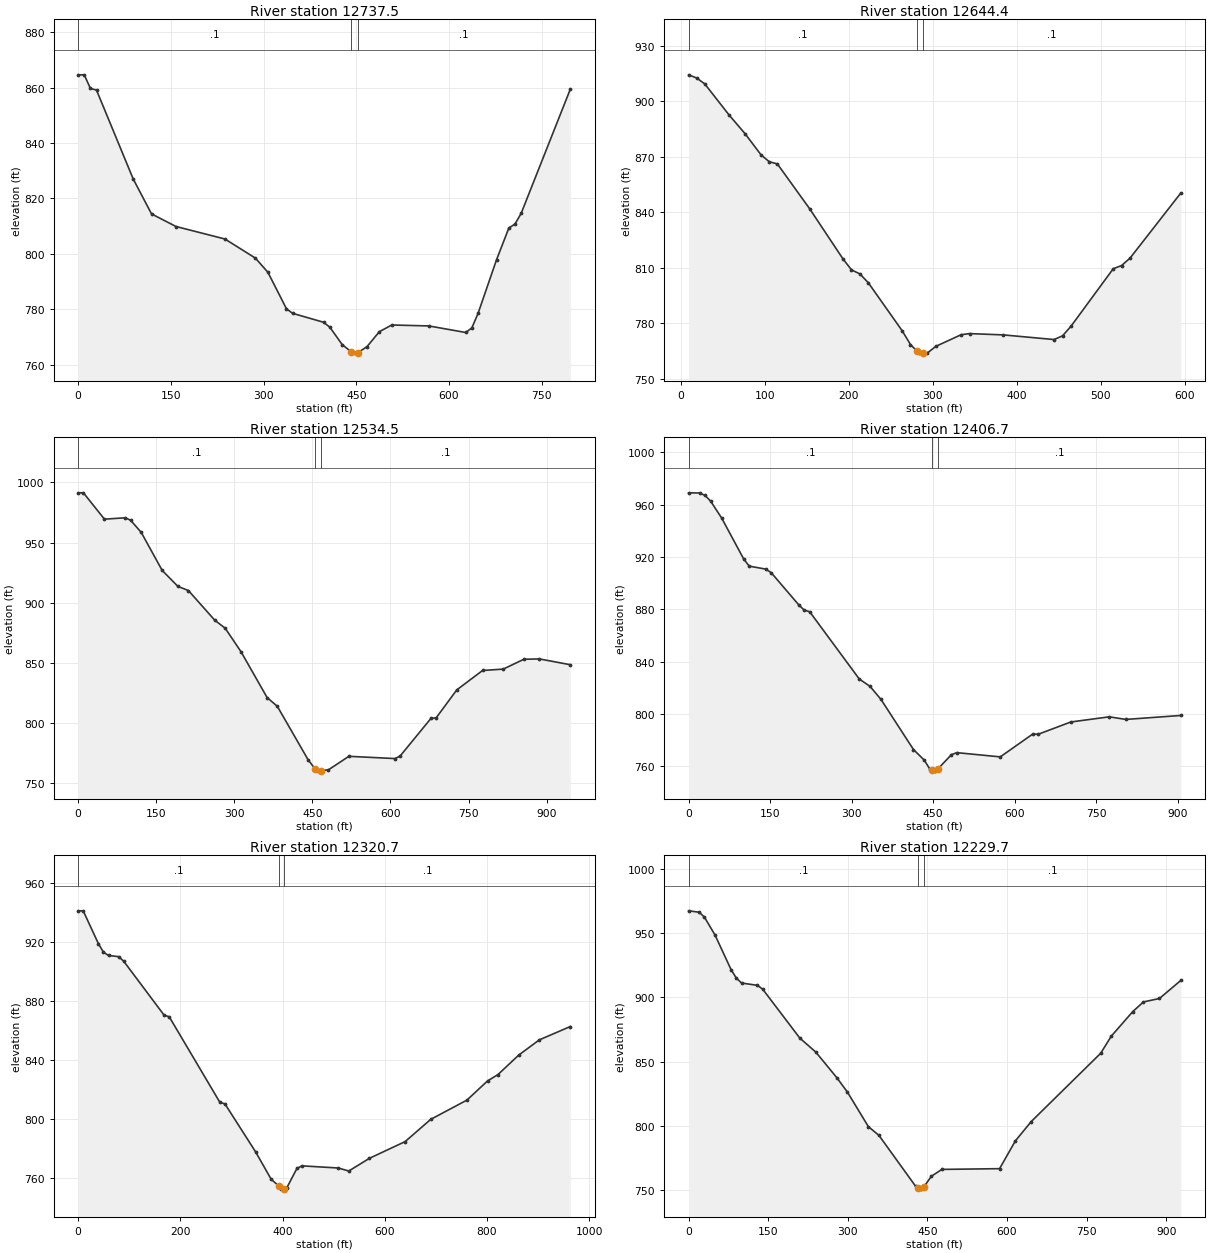
Type RM Length L Ch R = 1 ,12737.5 ,115.3,93.1,70.2
XS GIS Cut Line= 4
     1590190.745      303368.273     1590205.347      303654.845
     1589959.647       303704.26     1589912.559      303958.807
#Sta/Elev= 30
       0  864.64     9.9  864.64    19.8  859.73    29.7  859.13    89.1  827.02
   118.7  814.43   158.3  809.87   237.5  805.36   286.9  798.44     307  793.36
   337.1  780.15   347.1  778.51   397.2  775.29   407.2  773.52   427.3  767.23
     442   764.6   447.3  764.15   452.7  764.32   467.4   766.5   487.4   771.9
   507.5  774.31   567.4  773.97   627.2   771.6   637.1  773.28   647.1  778.51
     677  797.87   696.9  809.32   706.8  810.76   716.8   814.6   796.4  859.48
#Mann= 3 , 0 , 0
       0      .1       0     442    .045       0   452.7      .1       0
Bank Sta=442,452.7
XS Rating Curve= 0 ,0
Exp/Cntr=0.3,0.1

Type RM Length L Ch R = 1 ,12644.4 ,119.1,109.9,100.6
XS GIS Cut Line= 4
     1590067.265       303373.57     1590006.259      303524.864
     1589930.613      303732.283     1589891.569      303939.702
#Sta/Elev= 30
     9.6  914.29    19.2  912.56    28.8   909.4    57.6  892.66    76.8  882.45
      96  870.89   105.6  867.34   115.2  866.13   153.5  841.96   193.2  814.83
   203.3   808.9   213.3  806.73   223.3  801.96   263.5  776.07   273.5  768.56
  280.98  765.09   283.6  763.92   288.9  763.96   293.6     764   303.6  767.57
   333.7  773.87   343.8  774.47   383.9  773.77   444.2  771.26   454.3  773.26
   464.3  778.39   514.6   809.5   524.6  811.26   534.7   815.3     595  850.43
#Mann= 3 , 0 , 0
     9.6      .1       0  280.98    .045       0   288.9      .1       0
Bank Sta=280.98,288.9
XS Rating Curve= 0 ,0
Exp/Cntr=0.3,0.1

Type RM Length L Ch R = 1 ,12534.5 ,126,127.8,129.6
XS GIS Cut Line= 4
     1589873.994      303182.295     1589844.232      303534.208
     1589873.515      303797.752     1589777.957      304110.605
#Sta/Elev= 30
       0  991.37    10.1  991.37    50.5  969.46    90.8   970.6   100.9  968.49
   121.1   958.5   161.4  926.83   191.7  913.51   211.9  910.05   262.4  885.39
   282.5  878.71   312.8  859.19     363  821.02   382.6  813.74   441.6  769.39
   455.9  761.21   461.2  759.81   466.5  760.29   480.8  760.89   520.1  772.14
   608.5  770.26   618.3  772.26   677.8  803.71   687.7  804.12   727.4  827.44
   776.9  843.54   816.6   844.7   856.2  852.88     886  853.18   945.5  848.33
#Mann= 3 , 0 , 0
       0      .1       0   455.9    .045       0   466.5      .1       0
Bank Sta=455.9,466.5
XS Rating Curve= 0 ,0
Exp/Cntr=0.3,0.1

Type RM Length L Ch R = 1 ,12406.7 ,79.9,86.1,92.2
XS GIS Cut Line= 5
     1589839.626      303230.761     1589728.473      303524.289
      1589734.65       303813.57     1589722.495      303902.433
     1589682.232      304111.073
#Sta/Elev= 30
       0  969.14    20.2  969.01    30.4   967.1    40.5  962.78    60.7   949.9
   101.2  918.61   111.4  913.07   141.7  910.79   151.9  908.08   202.5  883.48
   212.6   879.4   222.7  878.18   313.9  826.73   333.8  821.05   353.8  811.14
   413.6  772.77   433.6   764.6   443.6  757.85   448.2  757.11   453.6  756.24
   458.9  758.09   483.5  768.85   493.5  770.37   573.3  767.14   633.1  784.63
   643.1  784.44     703  793.83   773.9  797.79   804.2  795.79   905.4  798.82
#Mann= 3 , 0 , 0
       0      .1       0   448.2    .045       0   458.9      .1       0
Bank Sta=448.2,458.9
XS Rating Curve= 0 ,0
Exp/Cntr=0.3,0.1

Type RM Length L Ch R = 1 ,12320.7 ,84.1,91,97.8
XS GIS Cut Line= 5
     1589792.186      303273.255     1589670.022      303565.624
     1589595.901      303818.188     1589520.406        303897.8
     1589453.147      304162.717
#Sta/Elev= 30
       0  941.41     9.9  941.41    39.6  919.17    49.5   913.4    59.4  911.13
    79.2  910.35    89.1  907.27   168.3  870.63   178.2  869.59   277.3  811.58
   287.2  810.53   347.2  778.02   377.6  759.48   392.5  754.86   397.9  752.72
   403.2  753.08     408  753.41   428.2  766.84   438.3   768.5   509.2  767.04
   529.5  764.99     570  773.62   639.9  784.96   689.8     800   760.7  813.07
   801.1  826.09   821.4  830.36   861.9  843.54   902.4  853.92   963.1  862.97
#Mann= 3 , 0 , 0
       0      .1       0   392.5    .045       0   403.2      .1       0
Bank Sta=392.5,403.2
XS Rating Curve= 0 ,0
Exp/Cntr=0.3,0.1

Type RM Length L Ch R = 1 ,12229.7 ,119,123.5,128
XS GIS Cut Line= 4
     1589797.868      303219.419     1589666.096      303465.881
     1589463.557      303746.507     1589177.369      303842.771
#Sta/Elev= 30
       0  967.21      20  966.12    29.9  962.25    49.9   948.3    79.9  921.61
    89.8  915.01    99.8  911.11   129.8   909.3   139.7  906.27   209.6  868.31
   239.6  857.48   279.5  837.47   299.3  826.33   338.8   799.5   358.6  792.76
   427.8  753.18   432.3  752.18   437.7  750.97   443.1  752.61   457.5  760.98
   477.2   766.3     586  766.87   615.7  788.43   645.7  803.51   776.5  856.53
   796.7  869.93   836.9  888.89   857.1  896.42   887.2  899.09   927.5  913.13
#Mann= 3 , 0 , 0
       0      .1       0   432.3    .045       0   443.1      .1       0
Bank Sta=432.3,443.1
XS Rating Curve= 0 ,0
Exp/Cntr=0.3,0.1

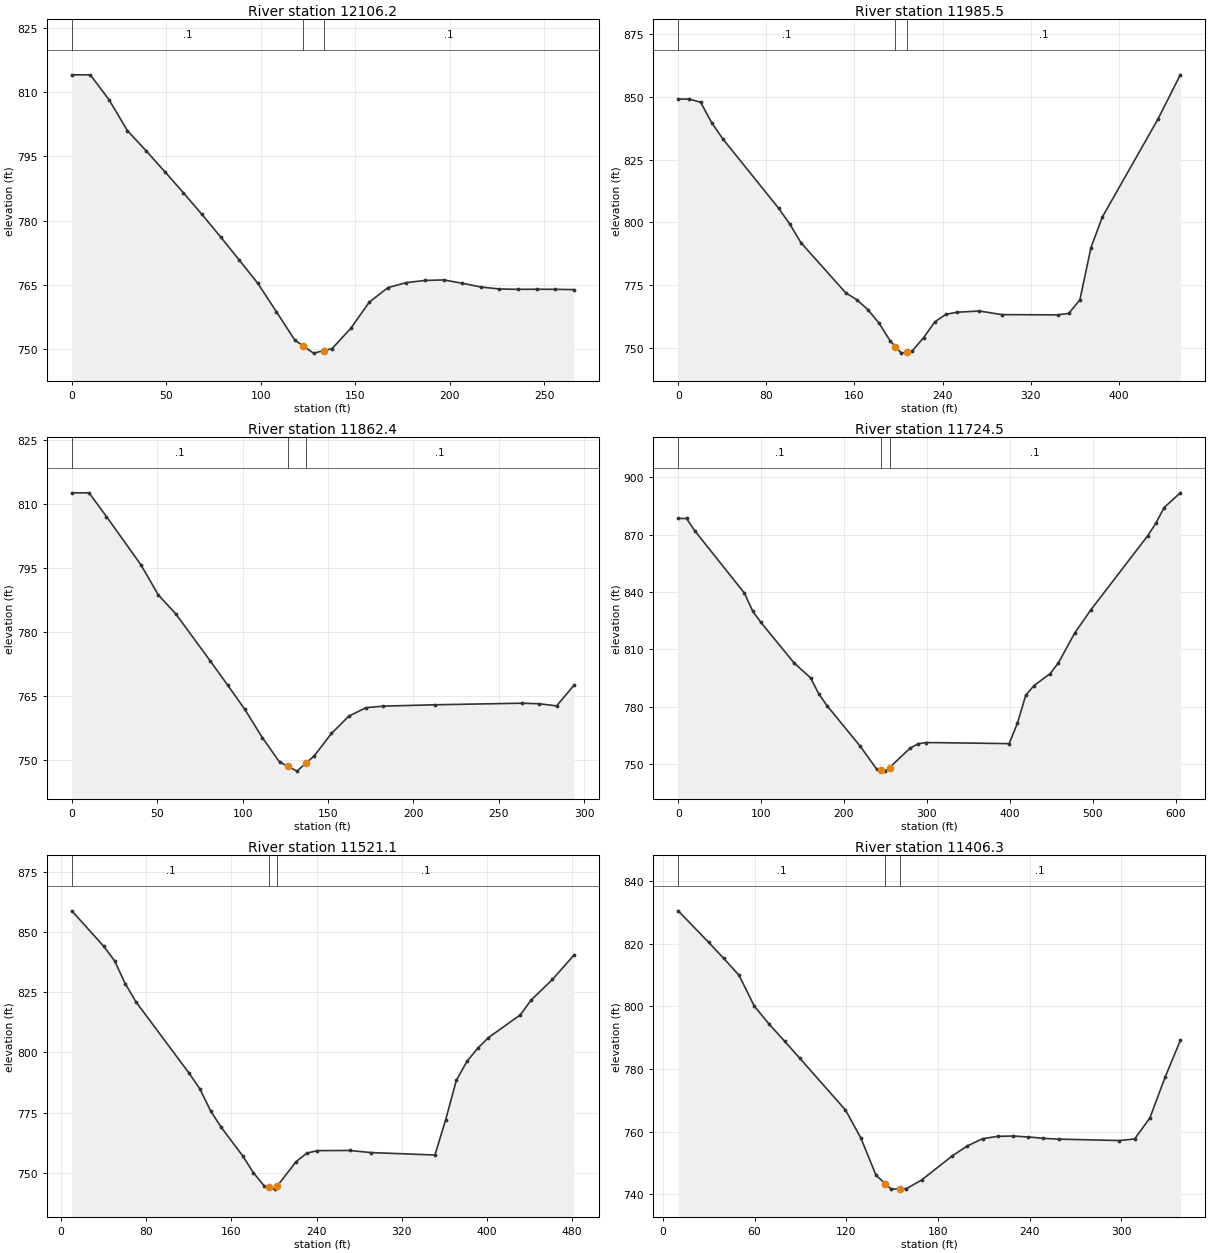
Type RM Length L Ch R = 1 ,12106.2 ,119.4,120.7,122.1
XS GIS Cut Line= 2
     1589581.659      303423.801     1589382.171      303599.498
#Sta/Elev= 30
       0  814.01     9.8  814.01    19.7  808.22    29.5  800.97    39.4  796.28
    49.2  791.46    59.1  786.51    68.9  781.46    78.8  776.21    88.6  770.86
    98.5  765.38   108.3  758.79   118.1  752.13   122.6  750.76     128  749.11
   133.4  749.69   137.8  750.16   147.7  754.89   157.5     761   167.4  764.39
   177.2  765.56   187.1  766.06   196.9  766.18   206.8   765.4   216.6  764.53
   226.4  764.07   236.3  763.99   246.1  764.01     256  763.99   265.8  763.92
#Mann= 3 , 0 , 0
       0      .1       0   122.6    .045       0   133.4      .1       0
Bank Sta=122.6,133.4
XS Rating Curve= 0 ,0
Exp/Cntr=0.3,0.1

Type RM Length L Ch R = 1 ,11985.5 ,121.9,123.1,124.4
XS GIS Cut Line= 2
     1589566.047      303295.066     1589204.894      303573.251
#Sta/Elev= 30
       0  849.18    10.1  849.18    20.3  847.94    30.4  839.75    40.5  833.32
    91.2  805.64   101.3  799.35   111.4  791.97     152  771.99   162.1  769.22
   172.2  765.26   182.3  759.89   192.5  752.79   197.2  750.52   202.6  747.92
     208  748.45   212.7  748.92   222.9  754.14     233  760.39   243.1   763.4
   253.3  764.23   273.5  764.71   293.8  763.27   344.4  763.17   354.6  763.75
   364.7  769.16   374.8  790.02     385  802.09   435.6  841.21   455.9  858.85
#Mann= 3 , 0 , 0
       0      .1       0   197.2    .045       0     208      .1       0
Bank Sta=197.2,208
XS Rating Curve= 0 ,0
Exp/Cntr=0.3,0.1

Type RM Length L Ch R = 1 ,11862.4 ,136,137.8,139.7
XS GIS Cut Line= 2
     1589433.415      303251.765     1589190.003      303416.481
#Sta/Elev= 24
       0  812.68    10.1  812.68    20.3  807.12    40.5  795.78    50.7   788.7
    60.8  784.33    81.1  773.22    91.2   767.6   101.3  761.87   111.5  755.27
   121.6  749.54   126.3  748.55   131.8  747.38   137.2  749.29   141.9  750.95
     152  756.21   162.2  760.29   172.3  762.27   182.4  762.63   212.8  762.95
   263.5  763.32   273.6  763.19   283.8  762.69   293.9  767.49
#Mann= 3 , 0 , 0
       0      .1       0   126.3    .045       0   137.2      .1       0
Bank Sta=126.3,137.2
XS Rating Curve= 0 ,0
Exp/Cntr=0.3,0.1

Type RM Length L Ch R = 1 ,11724.5 ,201,203.4,205.8
XS GIS Cut Line= 3
     1589457.426      303096.244     1589081.631      303303.663
     1588947.419      303418.354
#Sta/Elev= 30
       0  878.43      10  878.43      20  871.98    79.9  839.37    89.8  830.05
    99.8  824.06   139.8  802.87   159.7   795.1   169.7  786.61   179.7  780.46
   219.6  759.32   239.6  747.25   244.1  746.83   249.6  746.32     255  748.17
   279.5  758.23   289.5  760.67   299.5  761.28   399.3  760.71   409.3  771.43
   419.3  786.02   429.2  791.01   448.9  797.35   458.7  802.93   478.3  818.45
   497.9  830.69   566.5  869.41   576.4     876   586.2   884.1   605.8  891.84
#Mann= 3 , 0 , 0
       0      .1       0   244.1    .045       0     255      .1       0
Bank Sta=244.1,255
XS Rating Curve= 0 ,0
Exp/Cntr=0.3,0.1

Type RM Length L Ch R = 1 ,11521.1 ,114,114.8,115.5
XS GIS Cut Line= 2
     1589341.546      302955.874     1588894.985      303136.451
#Sta/Elev= 30
      10  858.96    40.1  844.17    50.2  838.16    60.2  828.68    70.2  821.14
   120.4  791.27   130.5  784.72   140.5  775.62   150.5   768.8   170.6  756.94
   180.6  749.96   190.7   744.5   195.2  743.88   200.7  743.11  203.27  744.55
   220.8  754.57   230.8  758.09   240.8  759.14     271   759.2     291  758.33
   351.2  757.31   361.3  772.02   371.3   788.4   381.3   796.3   391.4  801.78
   401.4  806.16   431.5  815.68   441.5  821.78   461.6  830.38   481.7  840.49
#Mann= 3 , 0 , 0
      10      .1       0   195.2    .045       0  203.27      .1       0
Bank Sta=195.2,203.27
XS Rating Curve= 0 ,0
Exp/Cntr=0.3,0.1

Type RM Length L Ch R = 1 ,11406.3 ,118.6,118.5,118.5
XS GIS Cut Line= 2
     1589252.228      302874.751     1588933.779      302990.051
#Sta/Elev= 29
      10  830.44    29.9  820.38    39.8  815.26    49.8  809.88    59.8  800.01
    69.7  794.17    79.7   788.8    89.7  783.32   119.5  766.86   129.5  757.98
   139.5  746.04  145.54  743.36   149.4  741.61     155   741.7   159.4  741.76
   169.3  744.51   189.3  752.19   199.2  755.38   209.2  757.69   219.1  758.46
   229.1  758.56   239.1  758.26     249  757.83     259  757.57   298.8  757.12
   308.8  757.62   318.8  764.35   328.7   777.3   338.7  789.06
#Mann= 3 , 0 , 0
      10      .1       0  145.54    .045       0     155      .1       0
Bank Sta=145.54,155
XS Rating Curve= 0 ,0
Exp/Cntr=0.3,0.1

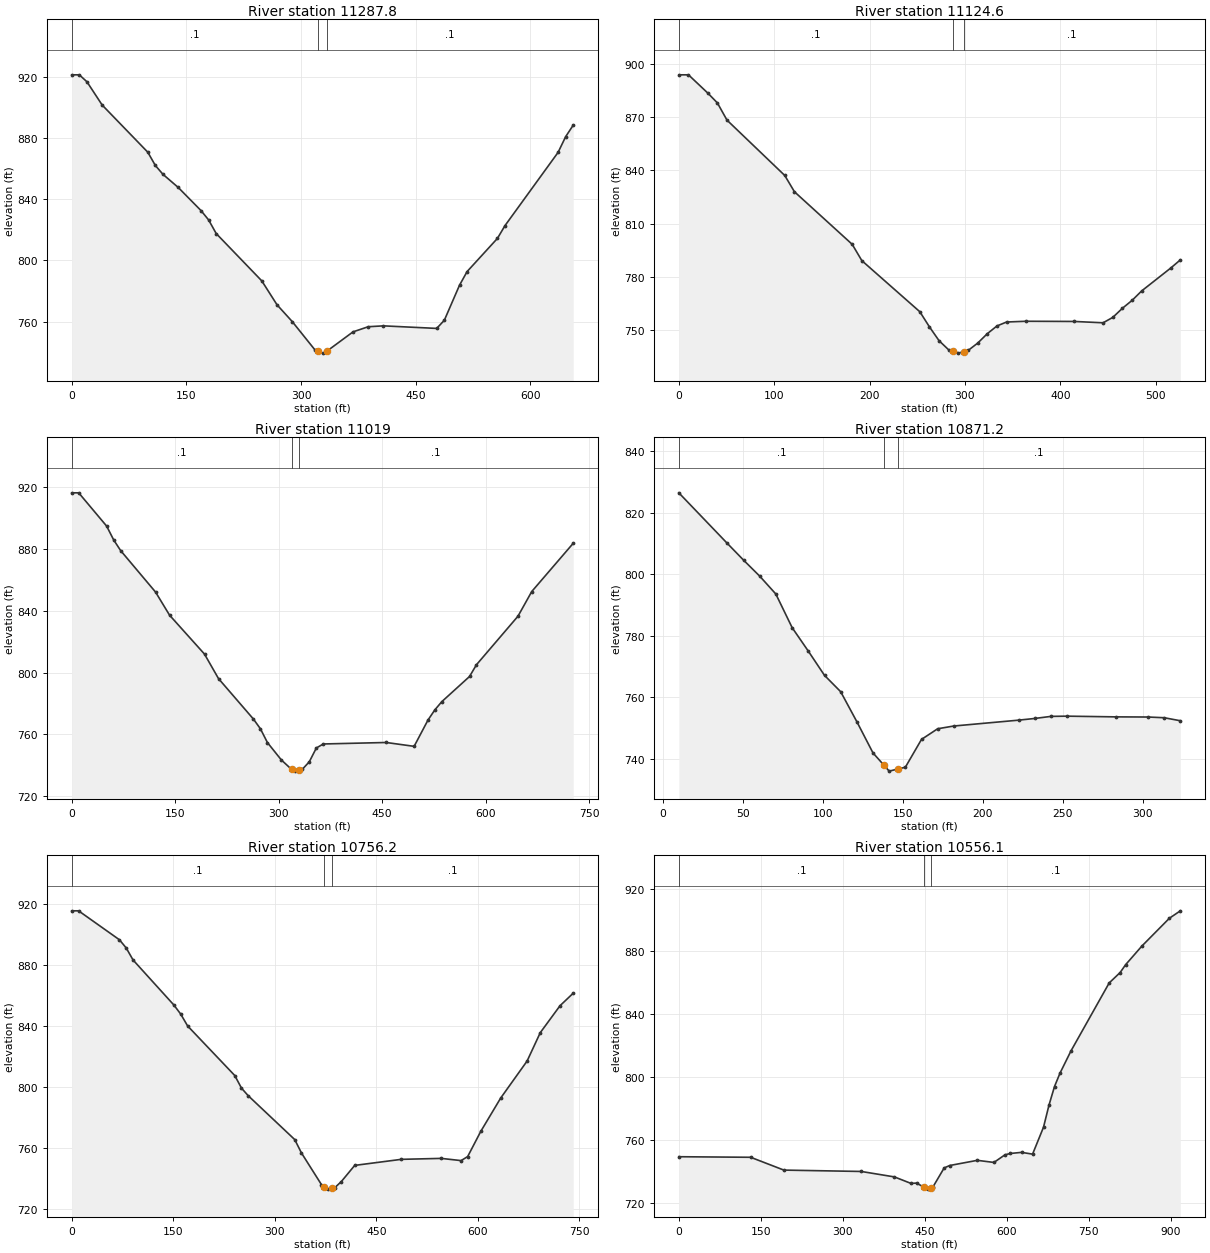
Type RM Length L Ch R = 1 ,11287.8 ,161.8,163.2,164.6
XS GIS Cut Line= 3
     1589361.068      302709.412     1588865.702      302889.988
     1588753.452      302953.434
#Sta/Elev= 30
       0  921.17     9.9  921.17    19.9  916.63    39.8  901.46    99.5  870.68
   109.4  862.01   119.4  856.22   139.3  847.68   169.1   832.6   179.1  826.48
     189   817.6   248.7  786.68   268.6  771.08   288.5  760.14   318.3  741.61
   322.7   740.7   328.3  739.54   333.8  740.81   368.1  753.43     388  756.77
   407.9  757.34   477.5  755.67   487.5  760.96   507.4  783.87   517.3  792.76
     557  814.42   566.9  822.76   636.4  870.58   646.3  880.83   656.2  888.34
#Mann= 3 , 0 , 0
       0      .1       0   322.7    .045       0   333.8      .1       0
Bank Sta=322.7,333.8
XS Rating Curve= 0 ,0
Exp/Cntr=0.3,0.1

Type RM Length L Ch R = 1 ,11124.6 ,104.2,105.6,107
XS GIS Cut Line= 3
     1589285.085      302622.993     1589103.898      302638.091
     1588773.095      302732.803
#Sta/Elev= 30
       0  893.75    10.1  893.75    30.3  883.52    40.4  877.96    50.5  868.26
   111.1  837.11   121.2  827.98   181.8  798.38   191.9  789.21   252.7  760.47
   262.8  751.94   272.9  744.15     283  739.01   287.6  738.17   293.1  737.17
   298.7  737.99   303.3  738.65   313.4  742.81   323.5  748.12   333.6  752.46
   343.7  754.68     364   755.1   414.6  754.99   444.9  754.24   455.1  757.29
   465.2  762.43   475.3  766.85   485.4  772.19   515.8  785.03   525.9  789.63
#Mann= 3 , 0 , 0
       0      .1       0   287.6    .045       0   298.7      .1       0
Bank Sta=287.6,298.7
XS Rating Curve= 0 ,0
Exp/Cntr=0.3,0.1

Type RM Length L Ch R = 1 ,11019   ,153.5,147.8,142.2
XS GIS Cut Line= 3
     1589287.861      302499.552     1588792.495      302604.482
     1588597.278      302706.971
#Sta/Elev= 30
       0  916.28    10.1  916.28    50.6  894.74    60.8  885.79    70.9  878.89
   121.5  852.05   141.8   837.1   192.4  811.94   212.7  796.08   263.3   769.9
   273.4  763.63   283.6  754.69   303.8  743.43   318.5  737.37   324.1  736.21
   329.7  736.87   334.2  737.41   344.3  742.27   354.5  751.19   364.6  753.78
   455.7  754.74   496.2  752.25   516.4  769.35   526.4  775.94   536.4  781.19
   576.5  797.44   586.5  805.02   646.7  836.45   666.7  852.43   726.8  883.65
#Mann= 3 , 0 , 0
       0      .1       0   318.5    .045       0   329.7      .1       0
Bank Sta=318.5,329.7
XS Rating Curve= 0 ,0
Exp/Cntr=0.3,0.1

Type RM Length L Ch R = 1 ,10871.2 ,118.2,115,111.7
XS GIS Cut Line= 2
     1589063.721      302356.813     1588778.215      302508.717
#Sta/Elev= 26
    10.1  826.48    40.4  810.04    50.5  804.63    60.6  799.42    70.7   793.6
    80.9  782.66      91  775.03   101.1  767.17   111.2  761.86   121.3  752.12
   131.4  741.96   138.3  737.94   141.5  736.05   147.1  736.75   151.6  737.31
   161.7  746.36   171.8  749.82   181.9  750.71   222.3  752.61   232.4  753.16
   242.6  753.84   252.7  753.91     283  753.68   303.2  753.63   313.3   753.4
   323.4  752.42
#Mann= 3 , 0 , 0
    10.1      .1       0   138.3    .045       0   147.1      .1       0
Bank Sta=138.3,147.1
XS Rating Curve= 0 ,0
Exp/Cntr=0.3,0.1

Type RM Length L Ch R = 1 ,10756.2 ,207.3,200.1,193
XS GIS Cut Line= 4
     1589192.692      302131.078     1589005.156      302228.701
     1588738.811      302431.226     1588602.158      302570.319
#Sta/Elev= 30
       0   915.3    10.1   915.3    70.5  896.33    80.5  890.97    90.6  883.11
     151  853.57   161.1  847.61   171.2  839.91   240.9  807.42   250.8  799.19
   260.6  794.27   329.5  765.48   339.4  756.74   368.9  736.03   373.1  734.75
   378.7  733.03   384.4  733.55   388.6  733.93   398.4  738.02   418.1  748.57
     487  752.54     546  753.16   575.3  751.71     585  754.35   604.5  770.96
   633.8  792.69   672.8  816.91   692.3  835.52   721.5  853.17     741  861.37
#Mann= 3 , 0 , 0
       0      .1       0   373.1    .045       0   384.4      .1       0
Bank Sta=373.1,384.4
XS Rating Curve= 0 ,0
Exp/Cntr=0.3,0.1

Type RM Length L Ch R = 1 ,10556.1 ,147.3,146,144.6
XS GIS Cut Line= 3
     1588974.001      301801.352     1588628.314      302348.182
     1588428.197      302529.668
#Sta/Elev= 30
       0  749.19   131.4  748.83   192.1  740.67   333.6   739.8   394.2  736.33
   424.5   732.2   434.7  732.39   449.2  729.62   454.9  728.55   460.6  729.44
     465  730.13   485.2  742.05   495.3  743.59   545.8  746.89   576.2  745.55
   596.4   750.4   606.5  751.27   626.7  751.96   646.9  750.84   666.9  768.01
     677  782.19     687   793.9     697  802.39     717  816.51     787  859.88
     807   866.5     817  871.48     847  883.45   897.1  901.08   917.1   905.8
#Mann= 3 , 0 , 0
       0      .1       0   449.2    .045       0   460.6      .1       0
Bank Sta=449.2,460.6
XS Rating Curve= 0 ,0
Exp/Cntr=0.3,0.1