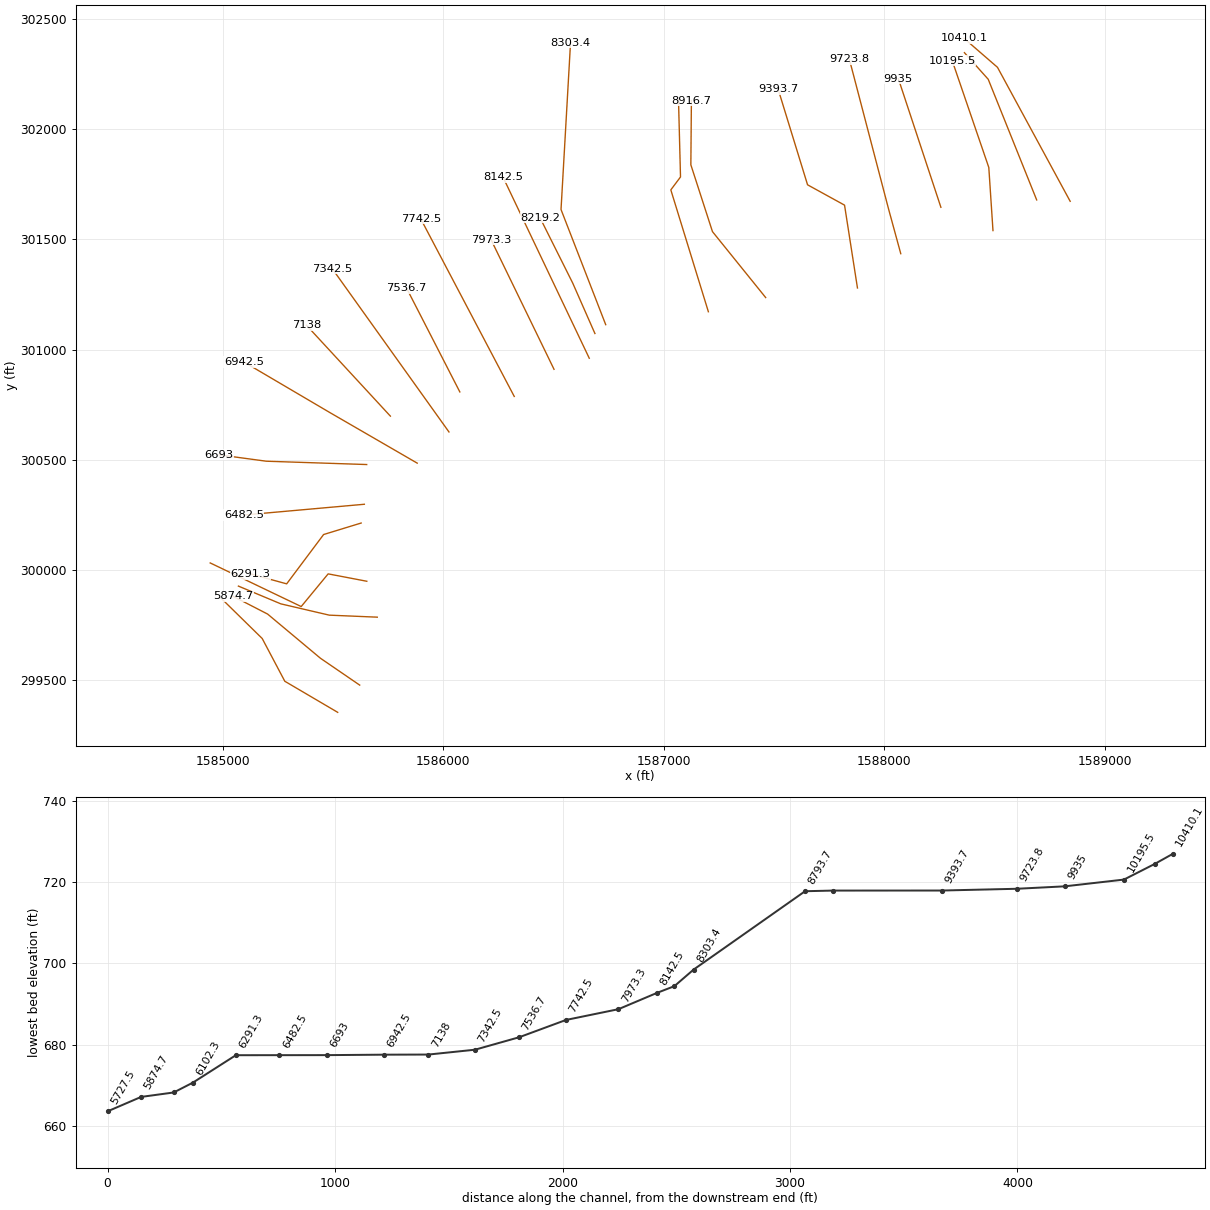
HEC-RAS study bgbrnch.prj: bgbrnch

--- bgbrnch.g01 (geometry) --- (continued)

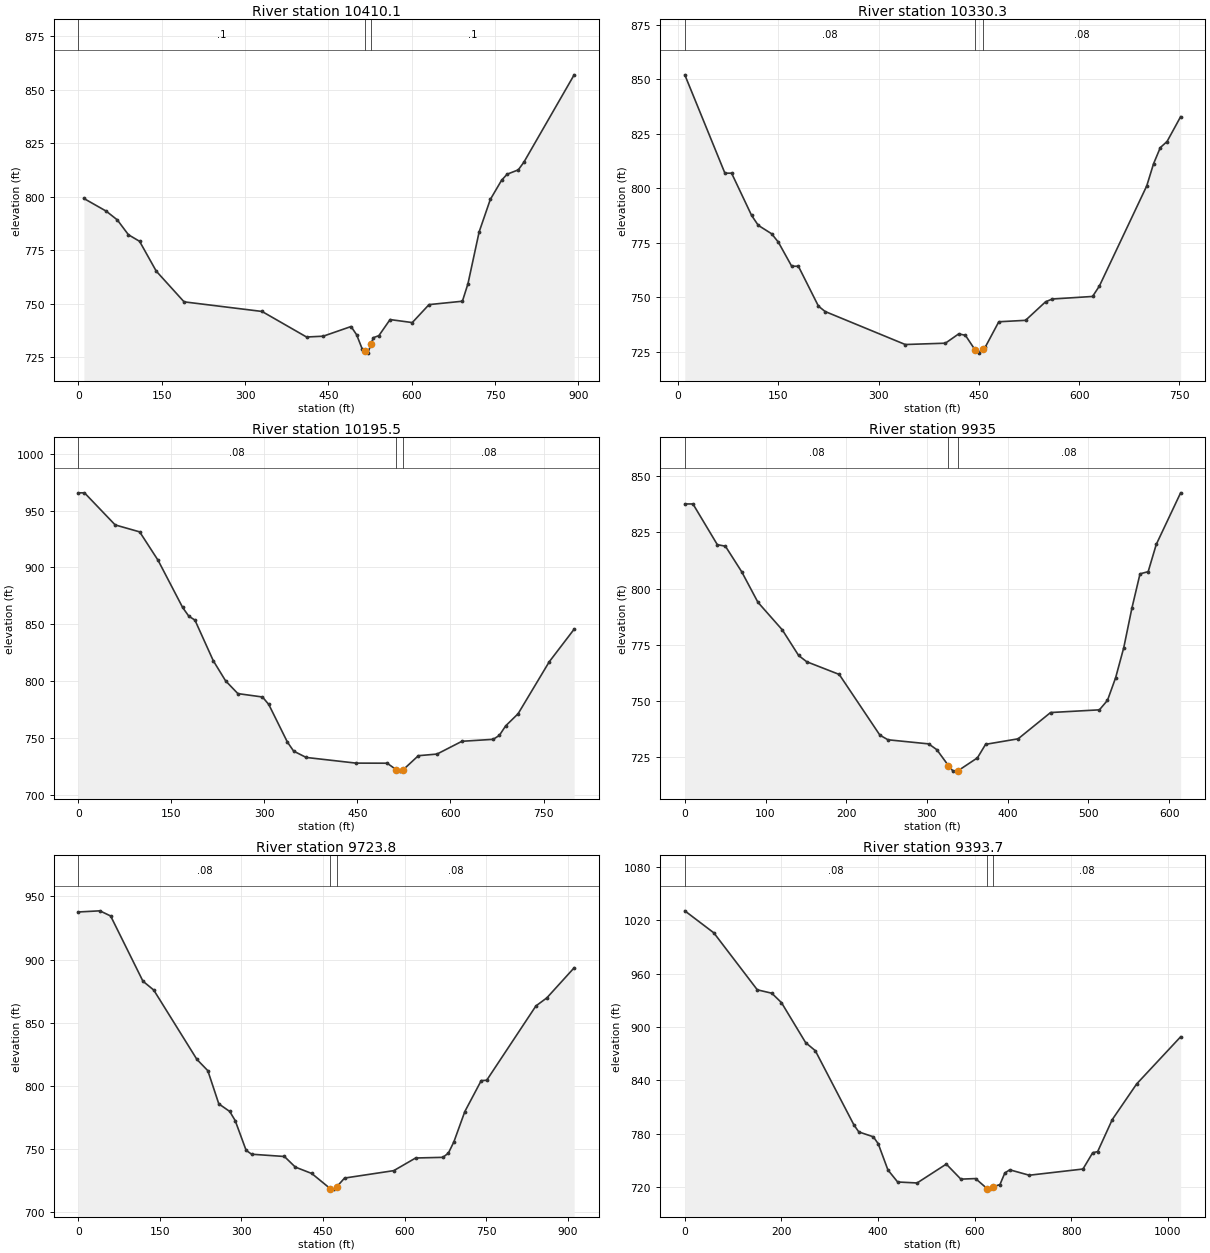
Type RM Length L Ch R = 1 ,10410.1 ,82.2,79.9,77.6
XS GIS Cut Line= 3
     1588842.215      301673.079     1588512.785      302280.695
     1588360.881      302412.467
#Sta/Elev= 30
      10  799.17    50.1  793.26    70.1  789.17    90.2  782.21   110.2  779.16
   140.2  765.23   190.3  750.87   330.6  746.38   410.7  734.44   440.7  734.82
   490.8  739.34   500.9  735.46   510.9  728.82   515.2     728   520.9  726.91
   526.6  731.02   530.9  734.12   540.9  735.09     561  742.59     601  741.19
   631.1  749.58   691.2  751.16   701.2  759.35   721.3  783.55   741.4  798.71
   761.6  807.64   771.6   810.5   791.7  812.53   801.8  816.11   892.3  856.94
#Mann= 3 , 0 , 0
       0      .1       0   515.2    .045       0   526.6      .1       0
Bank Sta=515.2,526.6
XS Rating Curve= 0 ,0
Exp/Cntr=0.3,0.1

Type RM Length L Ch R = 1 ,10330.3 ,135.8,134.8,133.7
XS GIS Cut Line= 3
     1588690.435       301679.18     1588470.815      302226.401
     1588362.835      302347.192
#Sta/Elev= 30
      10  852.13      70     807      80     807   109.9  787.63   119.9  783.06
   139.9  779.19   149.9  775.37   169.9   764.3   179.9   764.3   209.9  745.99
   219.9  743.52   339.8  728.37   399.8  728.98   419.7  733.24   429.7  732.62
     444  726.02   449.7  724.42   455.5   726.1   459.7  727.32   479.7  738.81
   519.7  739.47   549.7  747.98   559.7  749.25     620  750.43   630.2  755.23
     701  801.15   711.2  811.33   721.3  818.73   731.4  821.53   751.7  832.92
#Mann= 3 , 0 , 0
      10     .08       0     444    .045       0   455.5     .08       0
#XS Ineff= 2 , 0
       0     420                       0
Permanent Ineff=
       F       F
Bank Sta=444,455.5
XS Rating Curve= 0 ,0
Exp/Cntr=0.3,0.1

Type RM Length L Ch R = 1 ,10195.5 ,260.7,260.5,260.2
XS GIS Cut Line= 3
     1588492.301      301540.183     1588473.405      301826.445
     1588307.348       302311.35
#Sta/Elev= 30
       0  965.58     9.9  965.58    59.4  937.33    98.9   931.2   128.6  906.15
   168.2  864.64   178.1     857     188  853.53   217.6  817.74   237.4   800.1
   257.2  788.84   296.9  785.84     307   779.3   337.1  746.12   347.2  738.19
   367.3  732.64   447.7  727.64   497.9  727.57   512.3  721.97     518  720.59
   523.8  721.84   548.2  734.17   578.3  735.61   618.5  746.86   668.8  748.58
   678.8  752.04   688.9  760.38     709   771.1   759.2  816.83   799.4  845.57
#Mann= 3 , 0 , 0
       0     .08       0   512.3    .045       0   523.8     .08       0
Bank Sta=512.3,523.8
XS Rating Curve= 0 ,0
Exp/Cntr=0.3,0.1

Type RM Length L Ch R = 1 ,9935    ,212.5,211.2,210
XS GIS Cut Line= 2
     1588256.225      301645.869     1588063.447      302229.083
#Sta/Elev= 30
       0  837.58    10.1  837.58    40.3   819.5    50.3  818.82    70.5  807.46
    90.6  793.91   120.8  781.65     141  770.29     151  767.51   191.3  761.87
   241.7  734.89   251.7  732.85   302.1  731.03   312.2  728.45   326.5  721.42
   332.3  718.93   338.1  719.02   362.5  724.83   372.6  730.83   412.9  733.28
   453.1  744.95   513.6  746.15   523.6  750.37   533.7  760.42   543.8  773.82
   553.8  791.24   563.9  806.54     574  807.51     584  819.59   614.2  842.52
#Mann= 3 , 0 , 0
       0     .08       0   326.5    .045       0   338.1     .08       0
Bank Sta=326.5,338.1
XS Rating Curve= 0 ,0
Exp/Cntr=0.3,0.1

Type RM Length L Ch R = 1 ,9723.8  ,329.2,330.1,330.9
XS GIS Cut Line= 3
     1588074.299      301435.465     1588019.523      301636.108
     1587841.387      302316.931
#Sta/Elev= 30
       0  937.68    39.6  938.59    59.4  934.51   118.8  882.91   138.7  875.87
     218  821.02   238.1  812.08   258.3  785.81   278.4  779.79   288.4   772.6
   308.5  749.05   318.6  745.96   378.9  744.16     399  735.76   429.2  730.71
   463.5  718.63   469.4  718.33   475.2  720.17   489.5  727.08     580  732.96
   620.2  742.97   670.4  743.49   680.5  746.87   690.6  755.81   710.7  779.75
   740.8  804.21   750.9   804.5   841.4  863.32   861.5  869.71   911.7  893.51
#Mann= 3 , 0 , 0
       0     .08       0   463.5    .045       0   475.2     .08       0
Bank Sta=463.5,475.2
XS Rating Curve= 0 ,0
Exp/Cntr=0.3,0.1

Type RM Length L Ch R = 1 ,9393.7  ,476.8,477.1,477.4
XS GIS Cut Line= 4
      1587877.99      301279.835     1587819.424       301655.63
     1587651.798      301747.844     1587518.038      302182.739
#Sta/Elev= 30
       0 1030.54    60.1 1005.81   150.1  941.81   180.2  937.97   200.2  927.38
   250.2  882.47   270.2  873.44   350.3   789.9   360.3  782.16   390.4  776.68
   400.5  768.87   420.6  739.41   440.7  725.93     481  724.82   541.4  746.01
   571.6  729.12     602  729.76   626.4  718.26   632.3   717.9   638.2  720.59
   652.5     723   662.6  736.01   672.8   739.6   713.2  733.52   824.4  740.48
   844.6  758.83   854.8  760.04   885.1  796.07   935.6   836.1  1026.6  889.02
#Mann= 3 , 0 , 0
       0     .08       0   626.4    .045       0   638.2     .08       0
Bank Sta=626.4,638.2
XS Rating Curve= 0 ,0
Exp/Cntr=0.3,0.1

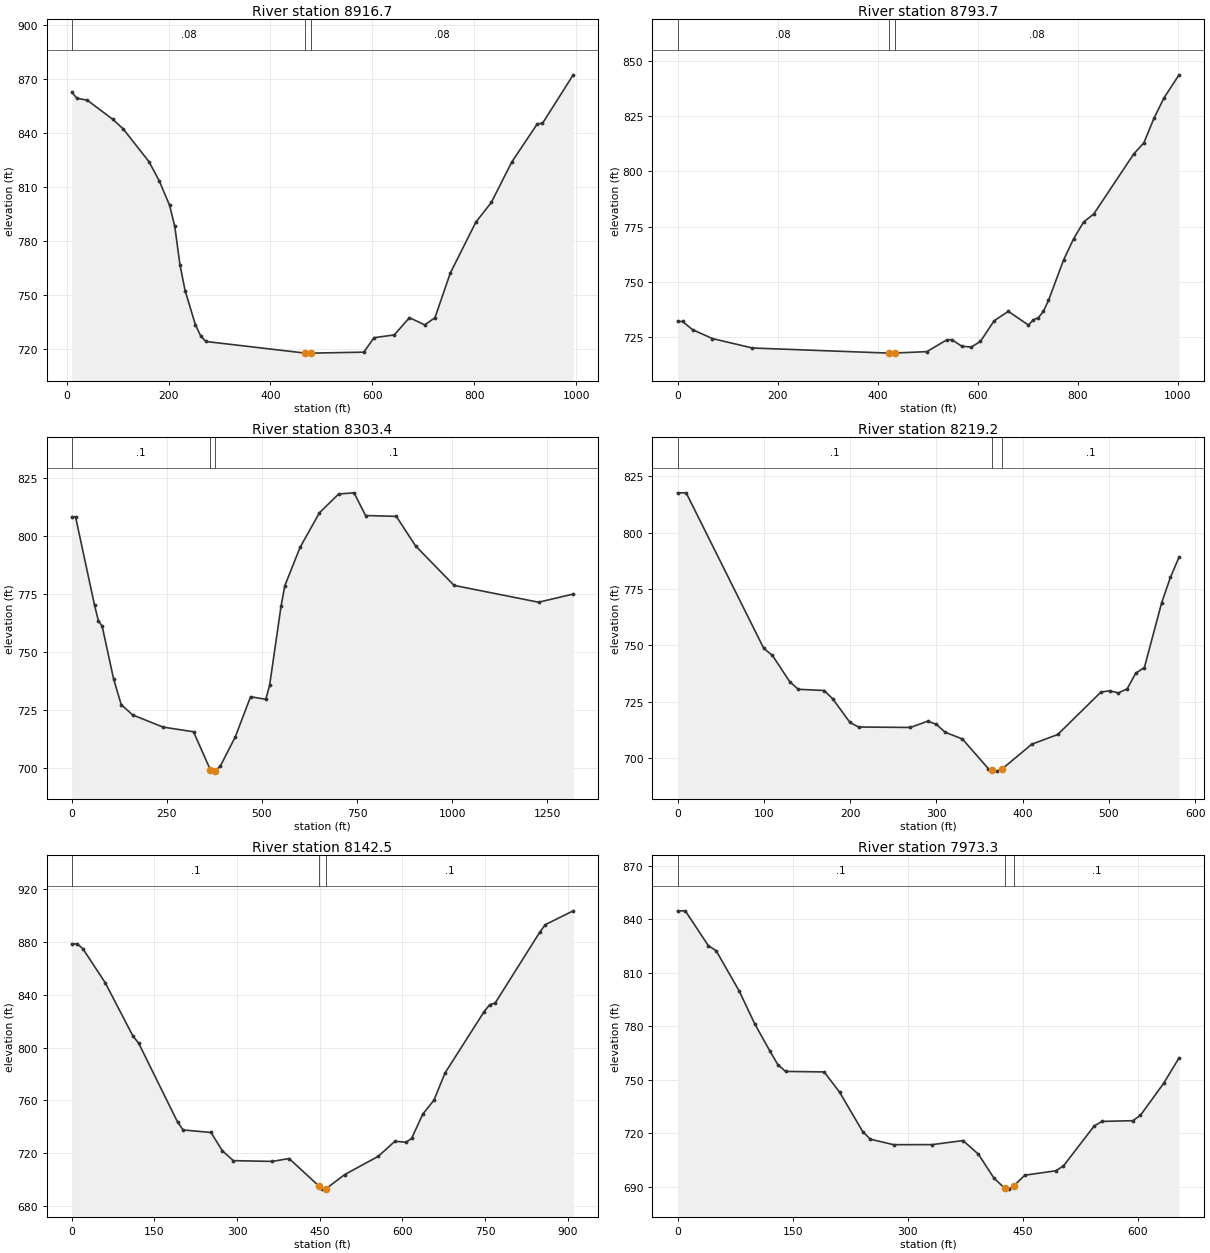
Type RM Length L Ch R = 1 ,8916.7  ,123.2,122.9,122.6
XS GIS Cut Line= 4
     1587461.847      301236.506     1587220.666      301535.544
      1587122.74      301838.647     1587125.215      302130.094
#Sta/Elev= 30
    10.1  862.81    20.2  859.42    40.4  858.39      91  847.66   111.2  842.38
   161.8  824.16     182  813.48   202.2   799.9   212.3  788.24   222.4  767.05
   232.5  752.67   252.7  733.75   262.9  727.57     273  724.37   467.8  717.92
  473.73  717.89   479.7   717.9   583.3  718.43   603.2  726.45     643  728.01
   672.8  737.59   702.7  733.59   722.8  737.54     753  762.36   803.2  790.69
   833.4  801.55   873.6  824.03   923.8  845.27   933.9  845.51   994.2  872.45
#Mann= 3 , 0 , 0
    10.1     .08       0   467.8    .045       0   479.7     .08       0
Bank Sta=467.8,479.7
XS Rating Curve= 0 ,0
Exp/Cntr=0.3,0.1

Type RM Length L Ch R = 1 ,8793.7  ,488.9,490.3,491.8
XS GIS Cut Line= 4
     1587202.136      301172.181      1587031.93      301724.892
     1587075.854      301783.458     1587066.703       302134.85
#Sta/Elev= 30
       0  732.05      10  732.05    29.9  728.36    69.8  724.32   149.6  720.05
   422.8  717.74   428.8  717.73   434.7  717.79   498.6   718.4   538.4  723.74
   548.4  723.83   568.4  720.87   587.5  720.46   605.8  723.05   633.2  732.39
   661.6  736.63   701.7  730.45   711.8  732.86   721.8  733.79   731.9  736.78
   741.9  741.59     772  759.85   792.1  769.49   812.2  777.11   832.3  780.67
   912.7  807.98   932.7  812.95   952.8  824.02   972.9  833.27    1003   843.7
#Mann= 3 , 0 , 0
       0     .08       0   422.8    .045       0   434.7     .08       0
Bank Sta=422.8,434.7
XS Rating Curve= 0 ,0
Exp/Cntr=0.3,0.1

Type RM Length L Ch R = 1 ,8303.4  ,82.4,84.2,86.1
XS GIS Cut Line= 3
     1586736.758      301113.504      1586534.22      301635.712
      1586577.35      302392.578
#Sta/Elev= 30
       0  808.21      10  808.21      60     770      70  763.41      80  760.96
     110  738.28     130  727.17     160  722.72     240  717.46   320.1  715.45
     364  699.15   370.1  698.46   376.1  698.59   390.1  700.48   430.1  713.33
   470.1  730.57   510.1  729.45   520.1  735.47   550.1  769.55   560.1  778.48
   600.5  795.13   651.1  809.93   701.6  818.05   742.1  818.55   772.4  808.76
   853.2  808.39   903.8  795.64  1004.9  778.61  1227.2  771.35  1318.2  774.87
#Mann= 3 , 0 , 0
       0      .1       0     364    .045       0   376.1      .1       0
Bank Sta=364,376.1
XS Rating Curve= 0 ,0
Exp/Cntr=0.3,0.1

Type RM Length L Ch R = 1 ,8219.2  ,77.1,76.7,76.3
XS GIS Cut Line= 3
     1586687.858      301073.352     1586587.199      301302.123
     1586438.955      301598.611
#Sta/Elev= 30
       0  817.56      10  817.56     100  748.68     110  745.61     130  734.01
     140  730.62     170  730.08     180  726.34   199.9  715.94   209.9  713.92
     270  713.73   290.1  716.52   300.2  715.06   310.2  711.62   330.3  708.61
   360.4  695.45   364.4  695.03   370.5   694.4   376.6  695.48   410.7  706.31
   440.8  710.62     491  729.44   501.1  729.93   511.1  729.02   521.2  730.78
   531.2  737.77   541.2  740.22   561.3  769.01   571.4  780.15   581.4  789.11
#Mann= 3 , 0 , 0
       0      .1       0   364.4    .045       0   376.6      .1       0
Bank Sta=364.4,376.6
XS Rating Curve= 0 ,0
Exp/Cntr=0.3,0.1

Type RM Length L Ch R = 1 ,8142.5  ,169,169.2,169.3
XS GIS Cut Line= 3
     1586662.221      300961.216     1586466.693      301372.061
     1586271.165      301782.906
#Sta/Elev= 30
       0  878.55    10.1  878.55    20.2  874.95    60.7  849.19   111.2  808.64
   121.3  803.46   192.1  743.52   202.2  737.58   252.8  735.67     273  721.93
   293.2  714.33     364  713.75   394.3  715.94   448.9  695.01     455  692.74
   461.1  692.96   495.4  703.81   556.1  717.55   586.4  729.01   606.7  728.29
   616.8  731.22     637  749.59   657.2  760.14   677.4  780.77   748.2   827.2
   758.3  832.43   768.4  833.79   849.3  887.46   859.4  893.19     910  903.64
#Mann= 3 , 0 , 0
       0      .1       0   448.9    .045       0   461.1      .1       0
Bank Sta=448.9,461.1
XS Rating Curve= 0 ,0
Exp/Cntr=0.3,0.1

Type RM Length L Ch R = 1 ,7973.3  ,230.2,230.8,231.5
XS GIS Cut Line= 2
     1586502.497      300910.966      1586216.99       301499.06
#Sta/Elev= 30
       0  844.77    10.1  844.77    40.2  825.19    50.3  822.42    80.5  799.72
   100.6  781.41   120.7  765.92   130.7  758.57   140.8  754.74   191.1  754.45
   211.2  743.12   241.4  720.95   251.4  716.72   281.6  713.66   331.9   713.7
   372.1  715.97   392.2  708.31   412.4  694.94   426.3   689.3   432.5  688.74
   438.6  690.67   452.6  696.55   492.8  699.01   502.9  701.67   543.1  724.15
   553.2  726.71   593.4  727.11   603.4  730.16   633.6  748.04   653.7  762.31
#Mann= 3 , 0 , 0
       0      .1       0   426.3    .045       0   438.6      .1       0
Bank Sta=426.3,438.6
XS Rating Curve= 0 ,0
Exp/Cntr=0.3,0.1

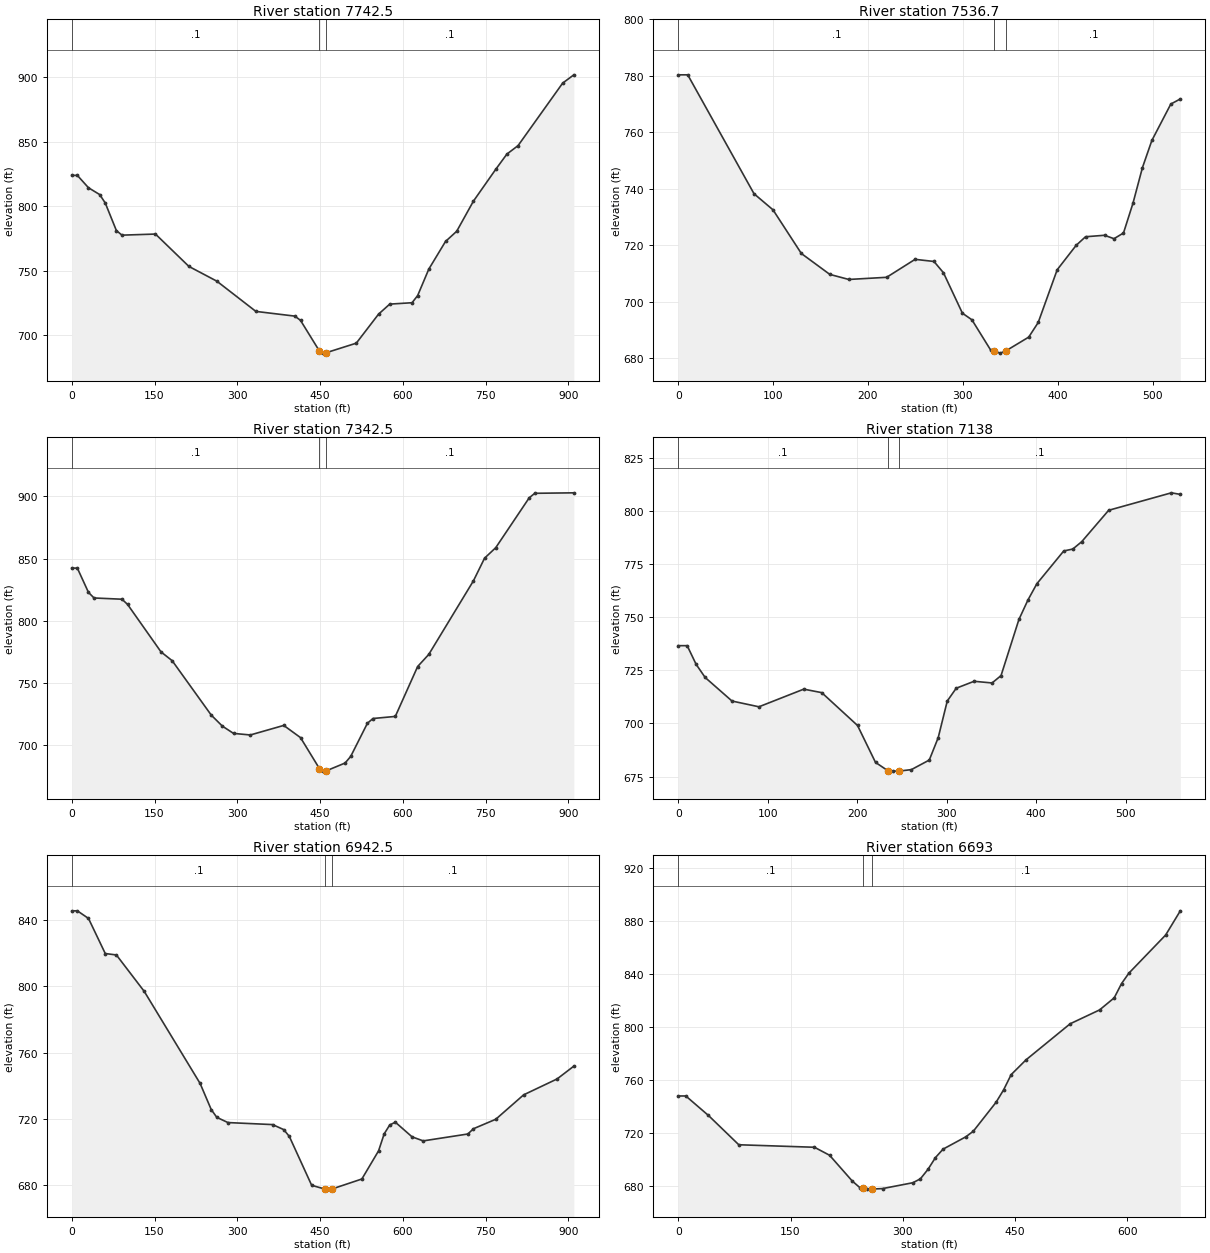
Type RM Length L Ch R = 1 ,7742.5  ,206,205.8,205.6
XS GIS Cut Line= 3
     1586322.142      300787.947     1586110.293      301190.619
     1585898.443      301593.291
#Sta/Elev= 30
       0  823.83    10.1  823.83    30.3  814.24    50.6  808.96    60.7  802.43
    80.9  781.03      91  777.51   151.7  778.36   212.3  753.28   262.9  741.86
   333.7  718.42   404.4  714.77   414.6  711.47   448.8  687.77     455  686.09
   461.2  686.42   515.7  693.81   556.1  716.33   576.3  724.07   616.8  725.15
   626.9  730.69   647.1  751.18   677.4  772.62   697.7  780.53     728  803.87
   768.4   828.5   788.7  840.35   808.9  846.89   889.8  895.36     910  901.75
#Mann= 3 , 0 , 0
       0      .1       0   448.8    .045       0   461.2      .1       0
Bank Sta=448.8,461.2
XS Rating Curve= 0 ,0
Exp/Cntr=0.3,0.1

Type RM Length L Ch R = 1 ,7536.7  ,191.3,194.2,197.2
XS GIS Cut Line= 2
     1586075.457      300808.476     1585833.875       301279.44
#Sta/Elev= 30
       0  780.36      10  780.36    79.9  738.26    99.9  732.57   129.8  717.11
   159.8  709.71   179.8  707.92   219.7  708.68   249.7  715.04   269.6  714.29
   279.6   710.3   299.6  695.97   309.6  693.64   329.6   682.8   333.4  682.44
   339.6  681.84   345.8  682.72   369.5  687.51   379.5  692.69   399.5  711.35
   419.5     720   429.4  723.04   449.4  723.56   459.4  722.35   469.4  724.37
   479.4  734.91   489.4  747.54   499.3  757.12   519.3  770.02   529.3  771.82
#Mann= 3 , 0 , 0
       0      .1       0   333.4    .045       0   345.8      .1       0
Bank Sta=333.4,345.8
XS Rating Curve= 0 ,0
Exp/Cntr=0.3,0.1

Type RM Length L Ch R = 1 ,7342.5  ,202,204.5,207
XS GIS Cut Line= 3
     1586026.273      300626.788     1585761.788      300997.021
     1585497.303      301367.254
#Sta/Elev= 30
       0  842.28    10.1  842.28    30.3  822.69    40.4  818.22      91  817.22
   101.1  813.05   161.8  774.77     182  767.71   252.8   723.9     273     715
   293.2  709.16   323.6   707.9   384.2  715.59   414.6  705.77   448.8  680.89
     455  678.78   461.2  679.01   495.4  685.31   505.6  690.65   535.9  717.37
     546  721.16   586.4  722.83   626.9  763.02   647.1  772.79     728  832.03
   748.2  850.28   768.4   858.7   829.1  898.89   839.2  902.52     910   902.9
#Mann= 3 , 0 , 0
       0      .1       0   448.8    .045       0   461.2      .1       0
Bank Sta=448.8,461.2
XS Rating Curve= 0 ,0
Exp/Cntr=0.3,0.1

Type RM Length L Ch R = 1 ,7138    ,189.5,195.5,201.4
XS GIS Cut Line= 2
     1585760.668      300698.666     1585379.993      301111.064
#Sta/Elev= 30
       0  736.62      10  736.62      20  727.83    30.1  721.65    60.1  710.57
    90.2  707.86   140.3  716.16   160.4  714.52   200.4  699.07   220.5   681.7
   234.3   677.8   240.5  677.59   246.8   677.6   260.6   678.3   280.6   682.8
   290.6  693.35   300.7  710.57   310.7  716.59   330.7  719.86   350.8  719.07
   360.8  722.53   380.8  748.94   390.9  758.12   400.9  765.78   430.9  781.18
     441  782.07     451  785.54   481.1  800.31   551.2  808.53   561.2   807.8
#Mann= 3 , 0 , 0
       0      .1       0   234.3    .045       0   246.8      .1       0
Bank Sta=234.3,246.8
XS Rating Curve= 0 ,0
Exp/Cntr=0.3,0.1

Type RM Length L Ch R = 1 ,6942.5  ,239.6,249.5,259.6
XS GIS Cut Line= 3
      1585882.29      300485.404     1585488.561      300713.473
     1585096.476      300944.323
#Sta/Elev= 30
       0  845.61    10.1  845.61    30.3  841.02    60.7  819.82    80.9  818.96
   131.4  796.94   232.6  741.38   252.8  725.58   262.9   720.9   283.1  717.75
     364  716.53   384.2  713.49   394.3  709.39   434.8  679.88   458.8  677.58
   465.1  677.56   471.4  677.62   525.8  683.68   556.1   700.7   566.2  710.91
   576.3  716.31   586.5  717.97   616.8  709.12     637  706.69   717.9  710.85
     728  714.02   768.5  719.75     819  734.49   879.7   744.1     910  751.83
#Mann= 3 , 0 , 0
       0      .1       0   458.8    .045       0   471.4      .1       0
Bank Sta=458.8,471.4
XS Rating Curve= 0 ,0
Exp/Cntr=0.3,0.1

Type RM Length L Ch R = 1 ,6693    ,208,210.5,212.9
XS GIS Cut Line= 3
     1585653.298      300479.046     1585198.623      300494.083
     1584984.677       300522.97
#Sta/Elev= 30
       0   747.9    10.1   747.9    40.4  733.14    80.9     711     182  709.11
   202.2  703.06   232.5  683.58   242.6  678.61   246.4  678.17   252.7  677.45
   259.1  677.54     273  677.86   313.4  682.28   323.5  685.21   333.6  692.35
   343.7  701.32   353.8  707.68   384.2     717   394.3  721.28   424.6   743.1
   434.7   752.5   444.8  764.03   464.7  775.24   523.6  802.48   562.9  812.96
   582.5  822.11   592.3  832.91   602.1  840.78   651.2  869.61   670.8  887.91
#Mann= 3 , 0 , 0
       0      .1       0   246.4    .045       0   259.1      .1       0
Bank Sta=246.4,259.1
XS Rating Curve= 0 ,0
Exp/Cntr=0.3,0.1

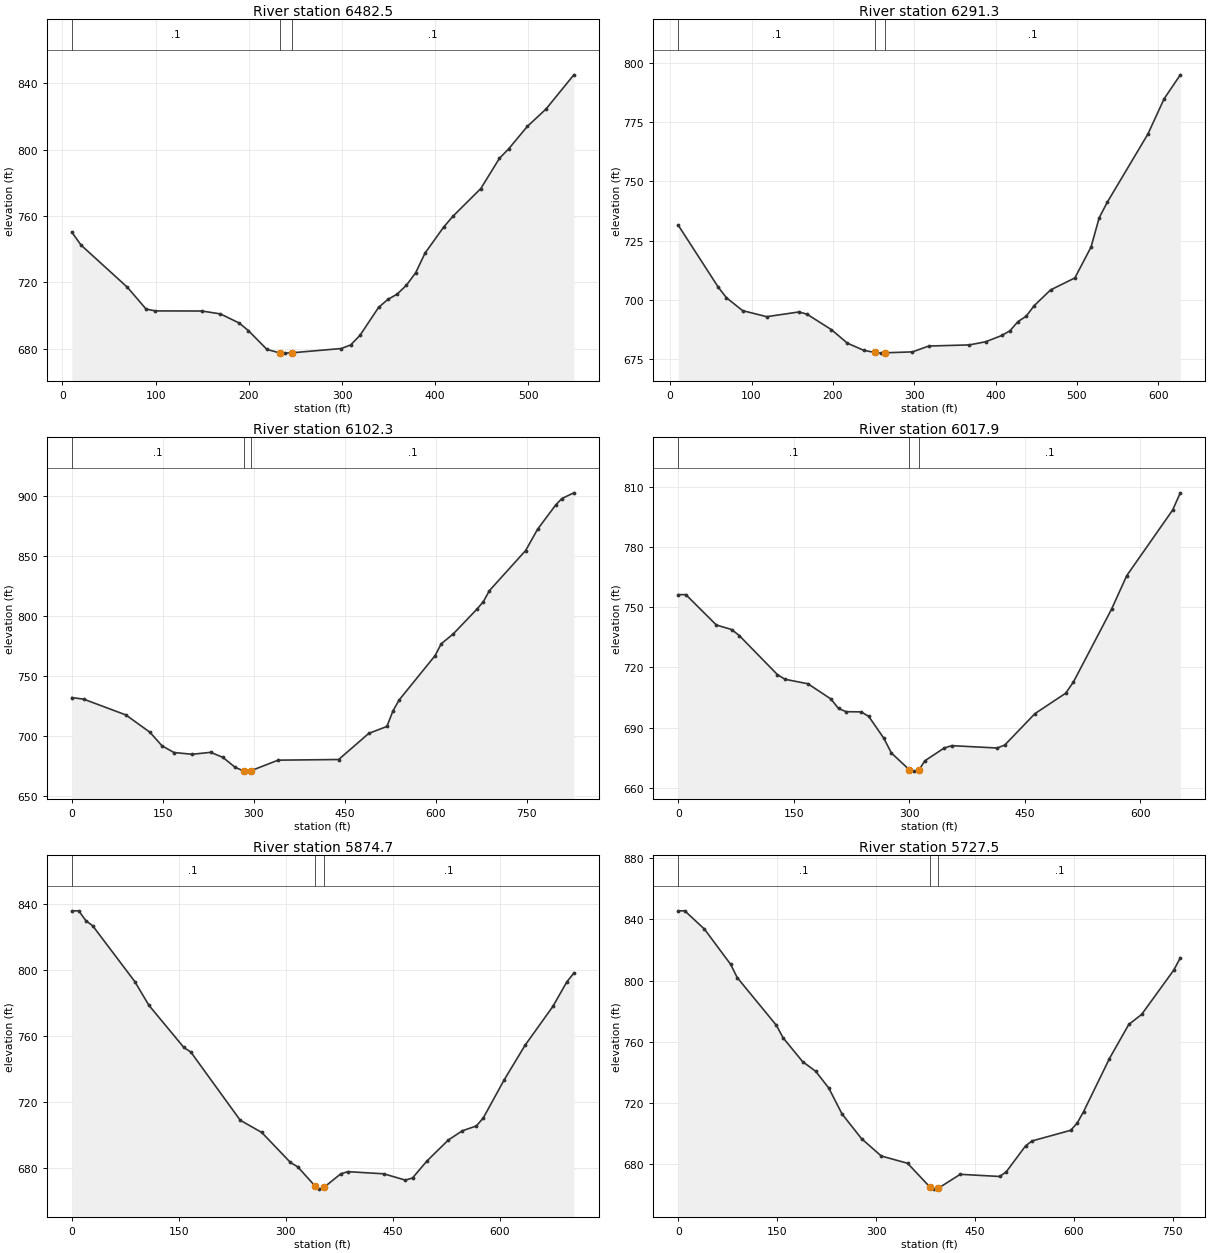
Type RM Length L Ch R = 1 ,6482.5  ,159.8,191.2,219.8
XS GIS Cut Line= 2
     1585642.744      300298.865     1585096.133       300250.06
#Sta/Elev= 30
      10  750.34      20  742.48    69.8  717.04    89.8  703.95    99.8  702.87
   149.7   702.8   169.6  701.05   189.6  695.58   199.6  690.98   219.5  679.64
   233.1   677.6  238.86  677.44   245.9  677.63   299.3  680.22   309.3  682.37
   319.3  688.14   339.2  704.93   349.2  709.78   359.2  712.97   369.2  718.37
   379.2  725.99   389.1  737.68   409.1  753.34   419.1  759.91     449  776.58
     469  794.81   478.9  800.48   498.9  813.99   518.9  824.43   548.8  845.04
#Mann= 3 , 0 , 0
      10      .1       0   233.1    .045       0   245.9      .1       0
Bank Sta=233.1,245.9
XS Rating Curve= 0 ,0
Exp/Cntr=0.3,0.1

Type RM Length L Ch R = 1 ,6291.3  ,197.7,188.9,185.4
XS GIS Cut Line= 4
     1585628.179       300213.75     1585457.974       300161.59
     1585290.513      299937.852     1585127.046      299982.759
#Sta/Elev= 30
     9.9   731.5    59.3   705.2    69.2  700.83      89  695.39   118.7  692.83
   158.2  694.83   168.1   693.9     198  687.39   217.9  681.62   237.9  678.62
   251.4  677.72  258.95  677.43   264.3  677.57   297.8  677.96   317.8  680.42
   367.7  680.91   387.6  682.22   407.6  684.89   417.6  686.88   427.5  690.76
   437.5  693.01   447.5  697.53   467.5  704.13   497.4  709.21   517.3  722.29
   527.3  734.64   537.3  741.24   587.1  769.97   607.1  784.92     627  795.04
#Mann= 3 , 0 , 0
     9.9      .1       0   251.4    .045       0   264.3      .1       0
#XS Ineff= 2 , 0
       0     232             312       0
Permanent Ineff=
       F       F
Bank Sta=251.4,264.3
XS Rating Curve= 0 ,0
Exp/Cntr=0.3,0.1

Type RM Length L Ch R = 1 ,6102.3  ,113.4,84.4,53
XS GIS Cut Line= 4
     1585653.813      299949.629     1585478.563      299983.148
     1585356.399      299834.905     1584943.975      300032.705
#Sta/Elev= 30
       0  731.99    19.8  730.66    89.2  717.53   128.9  703.09   148.7  691.84
   168.5  686.21   198.6  684.74     229  686.36   249.2  682.16   269.4  673.87
   283.2  670.85   289.6  670.69   296.1  671.16   340.2  679.83   440.1  680.38
   489.8  702.17   519.7  707.93   529.6  720.86   539.6  729.85   599.2  767.04
   609.2  776.83   629.1  785.08   668.8  806.09   678.8  812.05   688.7  821.15
   748.4  854.57   768.3  872.44   798.1  892.61     808  897.84   827.9  902.65
#Mann= 3 , 0 , 0
       0      .1       0   283.2    .045       0   296.1      .1       0
#XS Ineff= 2 , 0
       0     275             300       0
Permanent Ineff=
       F       F
Bank Sta=283.2,296.1
XS Rating Curve= 0 ,0
Exp/Cntr=0.3,0.1

Type RM Length L Ch R = 1 ,6017.9  ,152.6,143.2,133.8
XS GIS Cut Line= 4
     1585701.397      299786.743     1585483.607      299795.894
     1585263.987      299847.139     1585071.819      299927.667
#Sta/Elev= 30
       0  756.27     9.9  756.27    49.5  741.13    69.4  738.87    79.3  735.85
   128.8  716.39   138.7  714.06   168.4  711.83   198.2  704.25   208.1  699.51
     218  697.91   237.6  697.81   247.4  695.54     267  684.62   276.8   677.3
   299.8  669.05   306.2  668.27   312.7  668.91  320.16  673.41   345.4  679.82
   355.3  680.97   414.1   679.8   423.9  681.26   463.3  696.99     503   707.1
     513  712.64   562.6  749.01   582.4  765.78   641.9  798.44   651.9  807.04
#Mann= 3 , 0 , 0
       0      .1       0   299.8    .045       0   312.7      .1       0
Bank Sta=299.8,312.7
XS Rating Curve= 0 ,0
Exp/Cntr=0.3,0.1

Type RM Length L Ch R = 1 ,5874.7  ,155,147.2,139.3
XS GIS Cut Line= 4
     1585621.575      299478.554     1585443.439      299600.565
     1585204.297      299800.663     1585048.122      299881.191
#Sta/Elev= 30
       0  835.85     9.8  835.85    19.6  829.98    29.4  826.74    88.3  792.98
     108  778.65     157  753.05   166.8  750.27     236  708.94   266.2  701.52
   306.4  683.32   316.5  680.73   340.2  669.37   346.7  667.18   353.2  668.19
   376.9  676.47   386.9  677.77   437.2  676.46   467.4  672.64   477.4  673.96
   497.6  684.24   527.7  697.02   547.3  702.55   566.8  705.46   576.5  710.31
   605.8  733.41   635.1  754.39   674.2  778.03   693.7  792.89   703.4  798.11
#Mann= 3 , 0 , 0
       0      .1       0   340.2    .045       0   353.2      .1       0
#XS Ineff= 2 , 0
       0                     387       0
Permanent Ineff=
       F       F
Bank Sta=340.2,353.2
XS Rating Curve= 0 ,0
Exp/Cntr=0.3,0.1

Type RM Length L Ch R = 1 ,5727.5  ,108.6,109.9,111.1
XS GIS Cut Line= 4
     1585521.868      299355.092     1585282.116      299496.015
     1585179.627      299690.013     1584991.119       299874.86
#Sta/Elev= 30
       0  845.67     9.9  845.67    39.7  833.74    79.5  810.67    89.4  802.03
     149  770.72   158.9  762.69   188.7  747.02   208.6  740.67   228.4  729.69
   248.3  712.89   278.1  696.61     308   685.3   347.9  680.54   381.3   665.2
   387.8  663.64   394.3  664.18   427.7  673.33   487.5  671.92   497.5  674.95
   526.8  691.93   536.6  695.15   595.3  702.12   605.1  706.83   614.8  714.34
     654  749.04   683.3  771.34   702.9  777.94   751.7  806.97   761.5  814.97
#Mann= 3 , 0 , 0
       0      .1       0   381.3    .045       0   394.3      .1       0
Bank Sta=381.3,394.3
XS Rating Curve= 0 ,0
Exp/Cntr=0.3,0.1