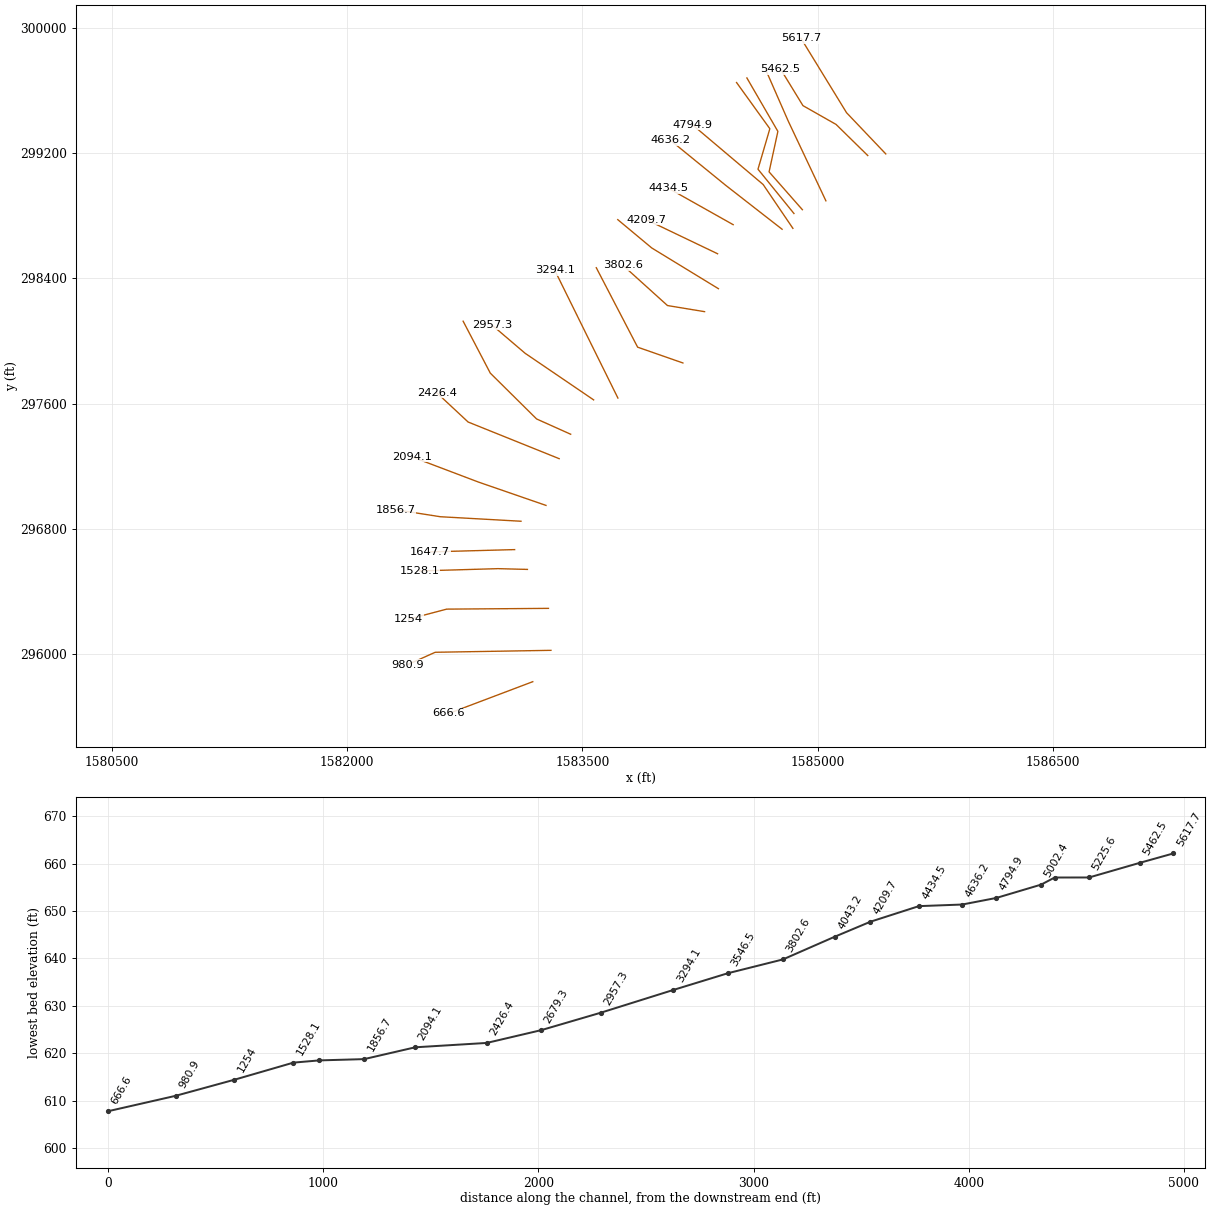
HEC-RAS study bgbrnch.prj: bgbrnch

--- bgbrnch.g01 (geometry) --- (continued)

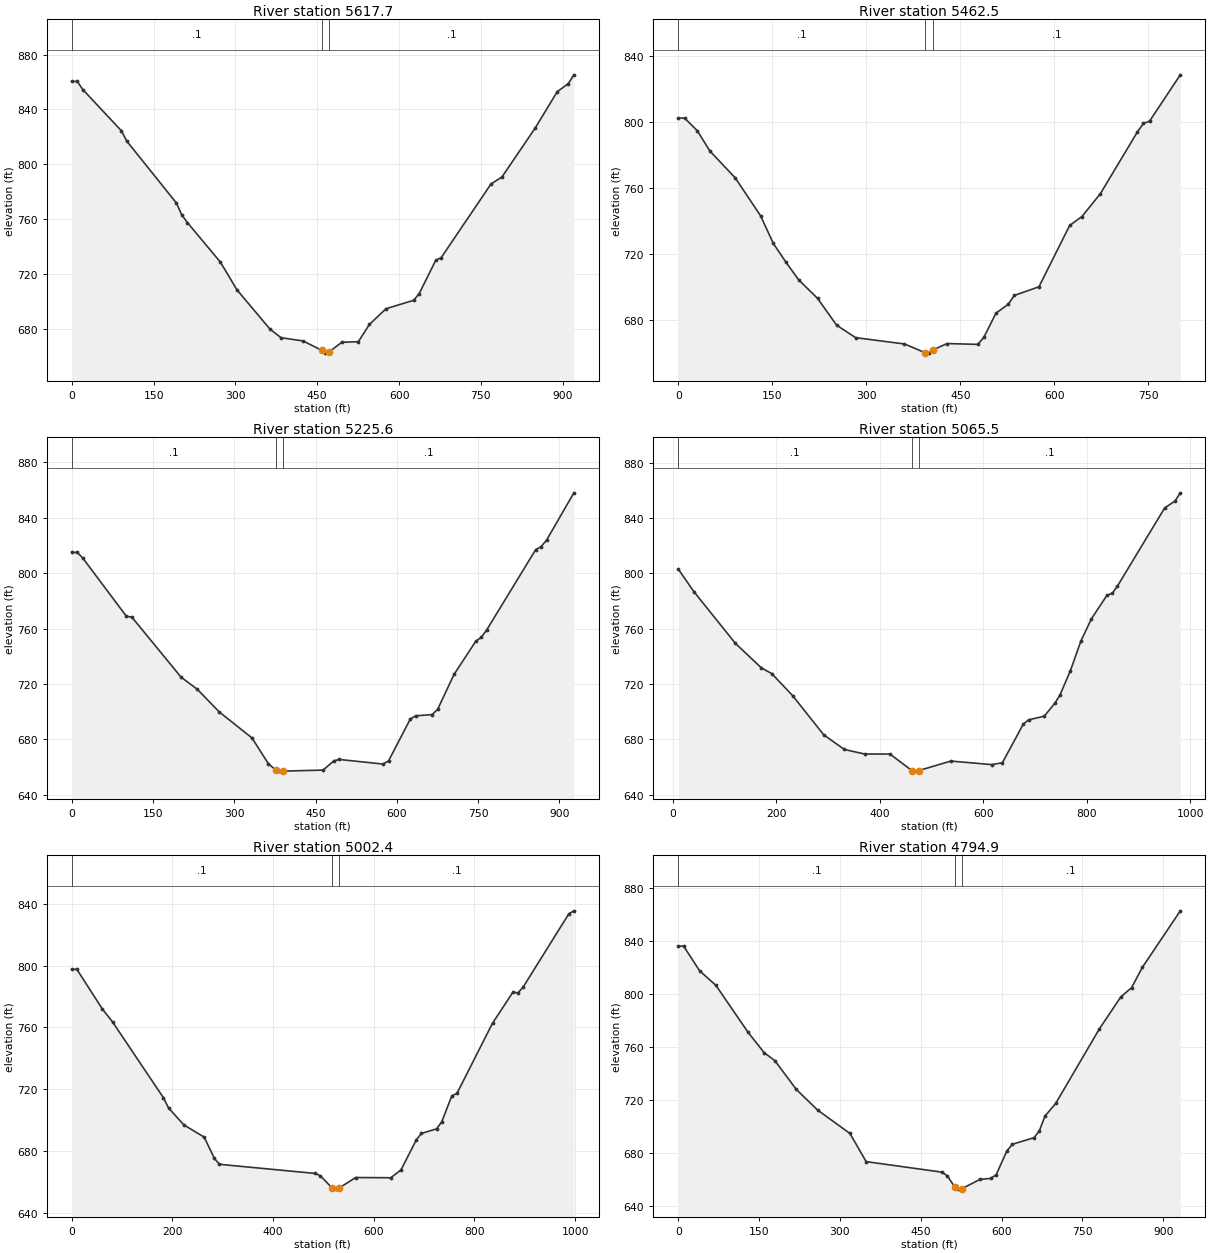
Type RM Length L Ch R = 1 ,5617.7  ,145.1,155.2,165.3
XS GIS Cut Line= 3
     1585434.996      299195.603     1585184.775      299459.032
     1584894.165      299934.276
#Sta/Elev= 30
       0  860.36    10.1  860.36    20.2  854.46    90.8  824.44   100.9   816.8
   191.8  771.67   201.8  762.91   211.9  757.44   272.5  728.52   302.8  708.34
   363.3  679.69   383.6  673.41   424.1  671.01   458.1  664.22   464.6  662.14
   471.1  662.85     495  670.04   525.4  670.49   545.6  683.07     576  694.53
   626.7  700.69   636.8  705.54   667.2   729.8   677.3  731.88   768.5  785.52
   788.7   790.7   849.5  826.35     890   852.9   910.3  858.77   920.4  865.19
#Mann= 3 , 0 , 0
       0      .1       0   458.1    .045       0   471.1      .1       0
Bank Sta=458.1,471.1
XS Rating Curve= 0 ,0
Exp/Cntr=0.3,0.1

Type RM Length L Ch R = 1 ,5462.5  ,250.4,236.9,223
XS GIS Cut Line= 4
     1585319.907      299185.435     1585118.182      299383.907
     1584906.696      299504.291     1584763.536      299738.553
#Sta/Elev= 30
       0   802.2    10.1   802.2    30.3  794.61    50.5  782.29      91  766.03
   131.4  743.13   151.6  726.52   171.8  715.13     192  704.49   222.4   693.2
   252.7  677.03     283  669.51   360.9  665.71   393.2  660.51   399.8  660.17
   406.4  662.15     429  665.96   477.7  665.45   487.4  669.67   506.9  684.35
   526.3  689.64   536.1  695.02   575.4  700.27   624.4  737.31     644  742.72
   673.4  756.52   732.2  793.67   742.1  798.98   751.9  800.37   800.9  828.33
#Mann= 3 , 0 , 0
       0      .1       0   393.2    .045       0   406.4      .1       0
Bank Sta=393.2,406.4
XS Rating Curve= 0 ,0
Exp/Cntr=0.3,0.1

Type RM Length L Ch R = 1 ,5225.6  ,174.2,160,145.8
XS GIS Cut Line= 3
     1585053.109      298895.862     1584812.341      299406.682
     1584667.309      299738.533
#Sta/Elev= 30
       0  814.99    10.1  814.99    20.2  810.98   100.8  768.87   110.9  768.28
   201.7  724.95   231.9  716.11   272.3   699.8   332.8  681.01     363  662.39
   376.6  657.87   383.2  657.07   389.8  657.09   463.9   657.8     484  664.55
   494.1  665.48   574.8  662.18   584.8  664.46   625.1  694.78   635.1  697.02
   665.3   697.9   675.4  701.66   705.6  726.84   745.8  750.81   755.9  753.64
   765.9  758.94   856.5  817.03   866.5  819.17   876.6  823.88   926.9     858
#Mann= 3 , 0 , 0
       0      .1       0   376.6    .045       0   389.8      .1       0
#XS Ineff= 2 , 0
       0                     504       0
Permanent Ineff=
       F       F
Bank Sta=376.6,389.8
XS Rating Curve= 0 ,0
Exp/Cntr=0.3,0.1

Type RM Length L Ch R = 1 ,5065.5  ,65.8,63.1,61.6
XS GIS Cut Line= 4
     1584903.036       298839.33     1584690.736      299080.912
     1584746.861      299339.576     1584549.203      299681.208
#Sta/Elev= 30
    10.1  803.11    40.2  786.86   120.6  749.41   170.9  731.66     191  727.53
   231.2  711.66   291.5  683.27   331.4  672.71   370.6  669.42   419.6  669.41
     462  657.44   468.8  657.06   475.3  657.47   537.3  664.34   616.7  661.77
   636.9   663.1   677.4  691.07   687.5  694.11   717.9  696.78   738.1  705.99
   748.2     712   768.5  729.71   788.7     751   808.9  767.01   839.3   784.2
   849.4  785.52   859.5  790.84   950.6  847.15   970.9  852.33     981  858.18
#Mann= 3 , 0 , 0
    10.1      .1       0     462    .045       0   475.3      .1       0
Bank Sta=462,475.3
XS Rating Curve= 0 ,0
Exp/Cntr=0.3,0.1

Type RM Length L Ch R = 1 ,5002.4  ,183,207.6,231
XS GIS Cut Line= 4
      1584849.35      298814.928     1584619.969      299097.994
     1584695.616      299356.658     1584483.317      299651.925
#Sta/Elev= 30
       0  797.61    10.1  797.61    60.7  771.96      81  763.62   182.2  714.56
   192.3     708   222.7  697.04   263.1  689.16   283.4  675.35   293.5   671.6
   484.1  665.68   494.1  664.16   517.4  656.22     524  655.56   530.7  656.17
     564  663.06   633.8  662.91     654  667.96   684.3  687.24   694.4  691.52
   724.8   694.5   734.9  698.98   755.1  715.86   765.2  717.37   835.9  762.76
   876.3  782.74   886.4  782.41   896.5  785.97   987.4  833.39   997.5  835.38
#Mann= 3 , 0 , 0
       0      .1       0   517.4    .045       0   530.7      .1       0
Bank Sta=517.4,530.7
XS Rating Curve= 0 ,0
Exp/Cntr=0.3,0.1

Type RM Length L Ch R = 1 ,4794.9  ,158.3,158.7,159.1
XS GIS Cut Line= 3
     1584842.633      298719.983     1584652.806      299000.269
     1584200.251        299383.5
#Sta/Elev= 30
       0  835.98      10  835.98    39.8  817.31    69.7  806.48   129.4  771.11
   159.3  755.65   179.2  749.67     219  727.94   258.9  712.26   318.6  694.74
   348.6   673.5   489.3  665.56   499.3  662.72   512.8  654.47   519.4  652.76
   526.1  653.05   559.6  660.07   579.7  660.85   589.8  663.55   609.9  681.73
     620  686.57   660.2  691.55   670.2  696.88   680.3  707.77   700.4  717.44
   780.8  773.21     821  797.61   841.1  804.66   861.2  820.03   931.5  862.57
#Mann= 3 , 0 , 0
       0      .1       0   512.8    .045       0   526.1      .1       0
Bank Sta=512.8,526.1
XS Rating Curve= 0 ,0
Exp/Cntr=0.3,0.1

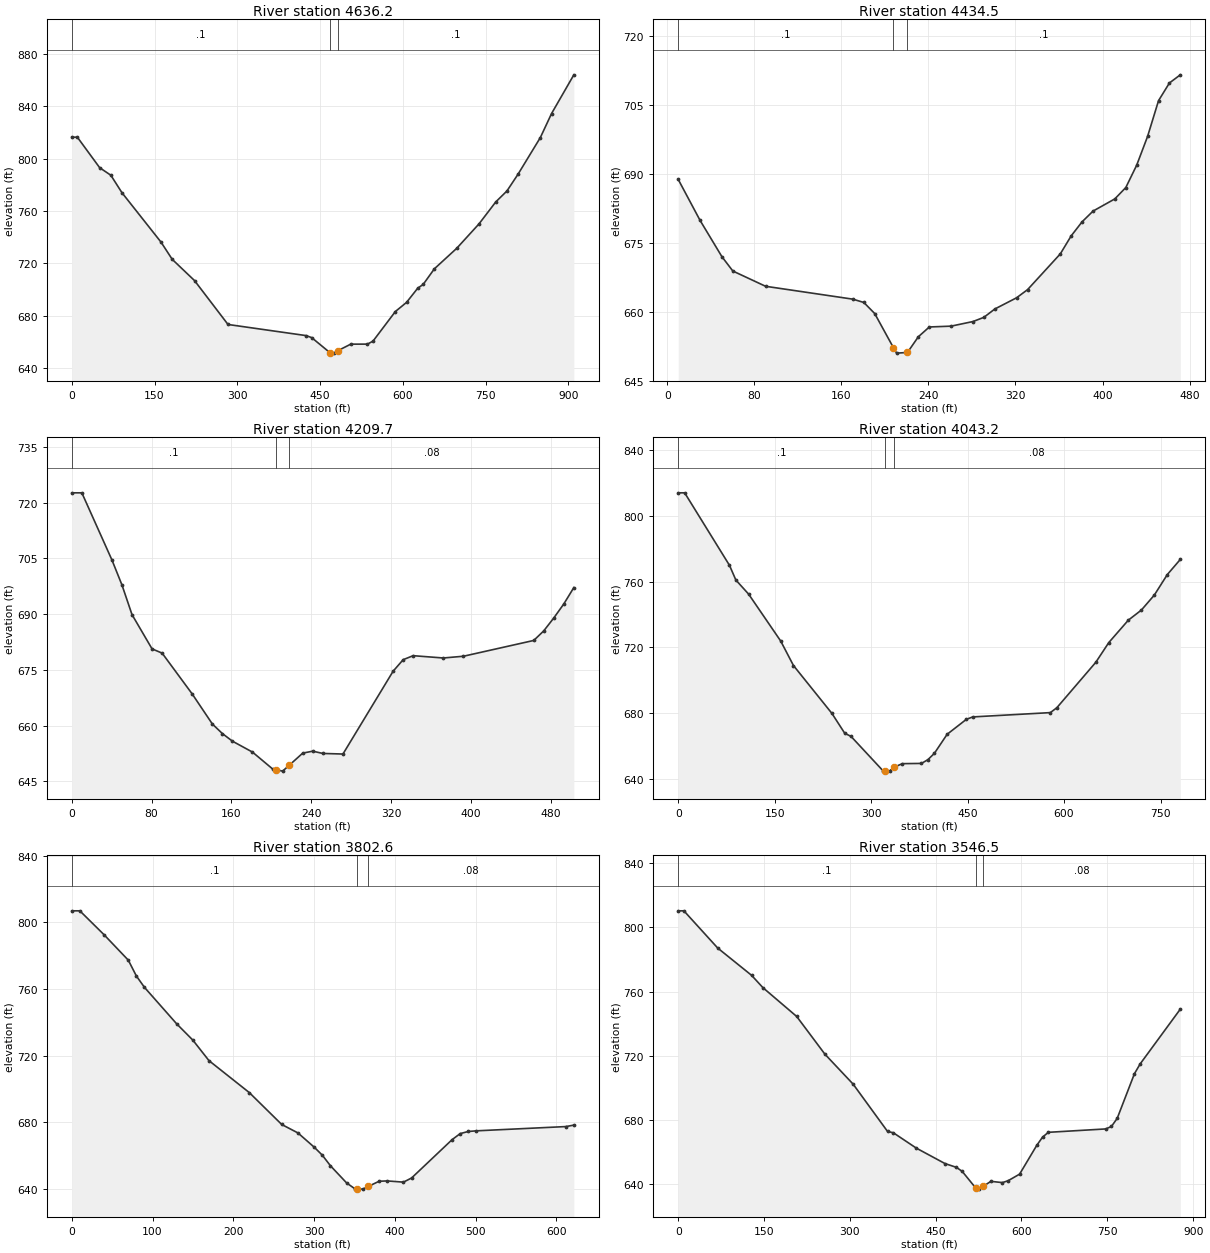
Type RM Length L Ch R = 1 ,4636.2  ,198.2,201.6,205
XS GIS Cut Line= 3
     1584773.777      298714.258     1584414.985      298994.281
     1584062.495      299281.952
#Sta/Elev= 30
       0  816.36    10.1  816.36    50.6  793.03    70.8  787.29      91  773.92
   161.8  736.17   182.1  723.02   222.5   706.8   283.2  673.26   424.8  664.76
   434.9  663.22   468.6  651.51   475.4  651.37   482.1  653.18   505.7  658.23
     536  658.25   546.1  660.56   586.6  683.17   606.8  690.12     627  700.92
   637.1  703.93   657.3   715.8   697.8  731.46   738.2  750.12   768.6  766.91
   788.8  775.25     809  788.11   849.4  816.08   869.7  834.41   910.1     864
#Mann= 3 , 0 , 0
       0      .1       0   468.6    .045       0   482.1      .1       0
#XS Ineff= 2 , 0
       0                   515.8       0
Permanent Ineff=
       F       F
Bank Sta=468.6,482.1
XS Rating Curve= 0 ,0
Exp/Cntr=0.3,0.1

Type RM Length L Ch R = 1 ,4434.5  ,223.5,224.8,226.1
XS GIS Cut Line= 2
     1584461.858      298743.435     1584051.107      298974.978
#Sta/Elev= 30
      10  688.81    30.1  679.89    50.2  671.99    60.2  668.89    90.3  665.57
   170.5  662.77   180.6  662.05   190.6  659.64  207.75  652.24   210.7  651.03
   220.7  651.17   230.7  654.59   240.8  656.72   260.8   656.9   280.9   657.9
   290.9  658.81     301  660.63     321  663.07   331.1  664.84   361.2  672.62
   371.2  676.54   381.2  679.59   391.3  681.93   411.3  684.58   421.4  687.05
   431.4  691.91   441.4  698.16   451.5  705.96   461.5   709.8   471.5  711.57
#Mann= 3 , 0 , 0
      10      .1       0  207.75    .045       0   220.7      .1       0
Bank Sta=207.75,220.7
XS Rating Curve= 0 ,0
Exp/Cntr=0.3,0.1

Type RM Length L Ch R = 1 ,4209.7  ,168.6,166.5,164.5
XS GIS Cut Line= 2
     1584362.236      298557.699     1583908.354      298775.489
#Sta/Elev= 30
       0  722.65    10.1  722.65    40.3  704.56    50.3  697.87    60.4  689.87
    80.5  680.65    90.6  679.51   120.8   668.5     141  660.42     151  657.86
   161.1  655.81   181.2  652.87   201.4  648.33   204.7  648.14   211.4  647.75
   218.2  649.37   231.6   652.6   241.6  653.12   251.7  652.51   271.9  652.35
   322.2  674.64   332.3  677.75   342.3  678.82   372.5   678.2   392.7  678.67
   463.2  682.92   473.2  685.49   483.3  688.97   493.4  692.77   503.4  697.16
#Mann= 3 , 0 , 0
       0      .1       0   204.7    .045       0   218.2     .08       0
#XS Ineff= 2 , 0
       0                   241.6       0
Permanent Ineff=
       F       F
Bank Sta=204.7,218.2
XS Rating Curve= 0 ,0
Exp/Cntr=0.3,0.1

Type RM Length L Ch R = 1 ,4043.2  ,244.3,240.6,236.8
XS GIS Cut Line= 3
     1584367.726      298334.419     1583943.127      298594.303
     1583725.858      298775.643
#Sta/Elev= 30
       0  813.99      10  813.99    79.7  769.85    89.6  760.92   109.5  752.31
   159.3  723.81   179.2  708.86     239  679.72   258.9  667.65   268.8  665.69
   318.6  644.73   321.8  644.68   328.6  644.58   335.4  646.93   348.5  649.13
   378.3  649.27   388.3  651.57   398.3  655.39   418.2  667.01     448  676.08
     458  677.58   578.7   680.2   588.8  683.18   649.4  710.84   669.6  722.84
     700  736.49   720.2   742.6   740.4  751.75   760.6  764.24   780.8  773.45
#Mann= 3 , 0 , 0
       0      .1       0   321.8    .045       0   335.4     .08       0
Bank Sta=321.8,335.4
XS Rating Curve= 0 ,0
Exp/Cntr=0.3,0.1

Type RM Length L Ch R = 1 ,3802.6  ,263.2,256.1,248.9
XS GIS Cut Line= 3
     1584279.451      298187.674      1584042.75      298226.718
     1583759.683      298482.941
#Sta/Elev= 30
       0  806.99      10  806.99      40  792.62      70  777.35      80  767.84
      90  761.02   129.9   739.1   149.9  729.33   169.9  716.99   219.9  697.77
     260  678.63   280.1  673.55   300.2     665   310.2  660.22   320.3  653.84
   340.4  643.49   350.4  640.07   353.6  639.98   360.5   639.8   367.3  641.46
   380.6  644.53   390.6  644.73   410.7     644   420.8   646.5     471  669.55
     481  673.16   491.1  674.44   501.1  674.82   611.7  677.38   621.7  678.25
#Mann= 3 , 0 , 0
       0      .1       0   353.6    .045       0   367.3     .08       0
Bank Sta=353.6,367.3
XS Rating Curve= 0 ,0
Exp/Cntr=0.3,0.1

Type RM Length L Ch R = 1 ,3546.5  ,252.8,252.4,252
XS GIS Cut Line= 3
     1584141.015      297859.818     1583852.412      297960.733
     1583588.868        298468.3
#Sta/Elev= 30
       0  810.36     9.9  810.36      69  787.16   128.2  770.16   147.9  762.51
   207.1   744.5   256.4     721   305.7  702.34   365.9  672.83     376  672.02
   416.1  662.46   466.3  652.82   486.3  650.46   496.4  647.93   519.6  637.76
   526.5  636.89   533.4  638.71   546.5  641.74   566.6  640.96   576.6  642.12
   596.7  646.24   626.8  664.24   636.8  669.29   646.9   672.3   747.2  674.41
   757.2  675.95   767.3  681.01   797.4  708.82   807.4  714.93   877.6  749.08
#Mann= 3 , 0 , 0
       0      .1       0   519.6    .045       0   533.4     .08       0
Bank Sta=519.6,533.4
XS Rating Curve= 0 ,0
Exp/Cntr=0.3,0.1

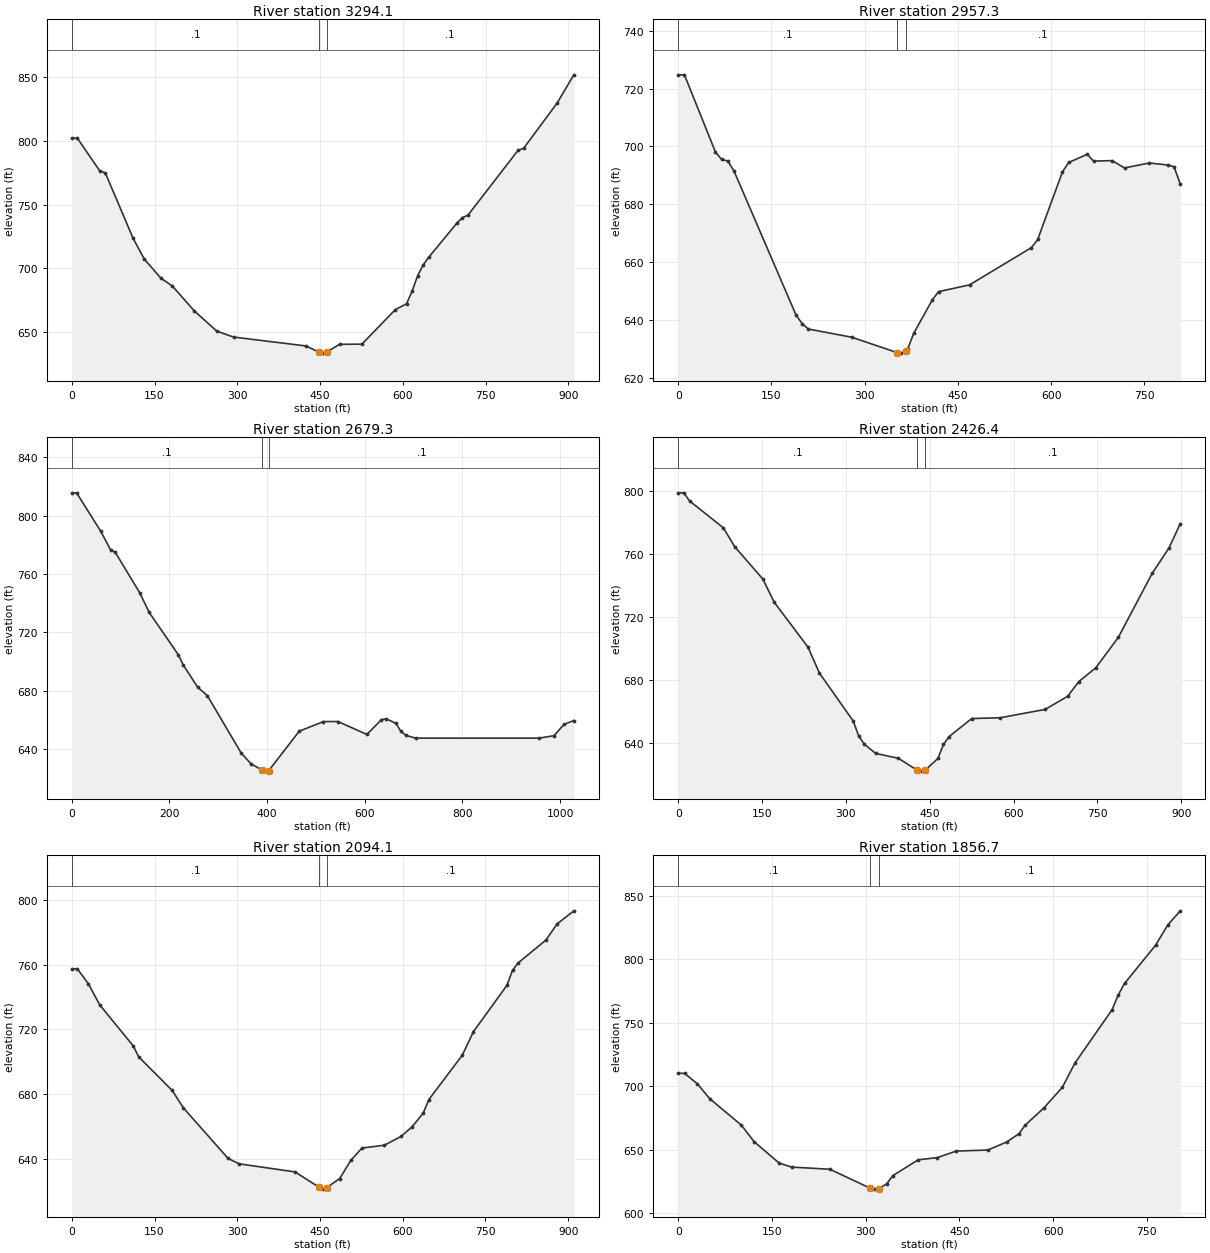
Type RM Length L Ch R = 1 ,3294.1  ,326.5,336.8,347.1
XS GIS Cut Line= 3
      1583726.64      297635.701     1583525.185      298043.673
     1583324.224      298451.888
#Sta/Elev= 30
       0  802.08    10.1  802.08    50.6  776.46    60.7  774.88   111.2  723.42
   131.4   707.2   161.8  692.06     182  686.18   222.4  666.38   262.9  650.63
   293.2  645.99   424.7     639   448.1  634.15     455  633.38   461.9  634.14
   485.3   640.3   525.8  640.42   586.4   667.5   606.7  672.08   616.8  681.87
   626.9  694.15     637  702.68   647.1  708.67   697.7  735.22   707.8  739.71
   717.9  741.52   808.9  792.54     819   794.1   879.7  829.59     910  851.75
#Mann= 3 , 0 , 0
       0      .1       0   448.1    .045       0   461.9      .1       0
Bank Sta=448.1,461.9
XS Rating Curve= 0 ,0
Exp/Cntr=0.3,0.1

Type RM Length L Ch R = 1 ,2957.3  ,281.7,278,274.3
XS GIS Cut Line= 3
     1583571.786      297623.982     1583134.986       297921.69
     1582922.501      298103.147
#Sta/Elev= 30
       0  724.74      10  724.74    59.8   698.1    69.8  695.49    79.8  694.98
    89.8  691.49   189.5  641.78   199.5  638.75   209.4  636.91   279.3  634.08
   352.1  628.79   359.1  628.59     366  629.49     369  629.88     379  635.44
   408.9     647   418.9  649.83   468.8  652.17   568.5  665.05   578.5  667.86
   618.4  691.25   628.4  694.45   658.3  697.29   668.3  694.94   698.3  695.09
   718.2  692.57   758.1  694.27   788.1  693.59     798  692.97     808   686.9
#Mann= 3 , 0 , 0
       0      .1       0   352.1    .045       0     366      .1       0
Bank Sta=352.1,366
XS Rating Curve= 0 ,0
Exp/Cntr=0.3,0.1

Type RM Length L Ch R = 1 ,2679.3  ,245,252.9,260.9
XS GIS Cut Line= 4
     1583425.373      297404.362     1583208.192      297501.971
     1582912.925      297794.798     1582739.669      298126.669
#Sta/Elev= 30
       0  815.57     9.9  815.57    59.5  789.15    79.4  776.54    89.3   774.7
   138.9  747.25   158.7  733.58   218.3  704.62   228.2  697.69   257.9  682.36
   277.7  676.61     347   637.3   366.8  630.03   389.5  625.64   396.5   624.9
   403.6  625.29   465.8  652.24   515.3  658.84     545  658.89   604.4  650.04
   634.2  660.16   644.1  660.79   664.1  657.58   674.2  652.08   684.3  649.39
   704.5   647.5   957.5   647.5   987.9  649.23  1008.1  656.91  1028.3  659.58
#Mann= 3 , 0 , 0
       0      .1       0   389.5    .045       0   403.6      .1       0
Bank Sta=389.5,403.6
XS Rating Curve= 0 ,0
Exp/Cntr=0.3,0.1

Type RM Length L Ch R = 1 ,2426.4  ,331.3,332.3,332.7
XS GIS Cut Line= 3
     1583352.166      297248.188     1582771.392      297482.449
     1582572.505      297668.394
#Sta/Elev= 30
       0  798.73    10.1  798.73    20.2   793.6    80.8  776.51     101  764.58
   151.5  744.01   171.7  729.37   232.3   700.8   252.5  684.51   313.1  654.02
   323.2   644.3   333.3  639.18   353.5  633.44   393.9  630.35   427.2  622.91
   434.3  622.21   441.4  622.64   464.6  630.22   474.7   639.1   484.8  644.15
   525.2  655.57   575.7  656.05   656.5  661.34   696.8  669.65     717  679.05
   747.2  687.75   787.6  707.06   848.1  747.65   878.3  763.81   898.5  779.23
#Mann= 3 , 0 , 0
       0      .1       0   427.2    .045       0   441.4      .1       0
Bank Sta=427.2,441.4
XS Rating Curve= 0 ,0
Exp/Cntr=0.3,0.1

Type RM Length L Ch R = 1 ,2094.1  ,231.9,237.4,243.5
XS GIS Cut Line= 3
     1583267.979      296949.646     1582837.774      297098.541
      1582412.44      297260.024
#Sta/Elev= 30
       0  757.47    10.1  757.47    30.3   748.1    50.6  735.19   111.3  709.86
   121.4     703   182.1  682.28   202.3  671.52   283.3  640.28   303.5  636.92
   404.7  631.93   448.1  622.53   455.2  621.29   462.4  622.24   485.6  627.82
   505.8     639     526  646.67   566.5  648.42   596.8  653.82     617  659.84
   637.2  668.26   647.3  676.61     708  704.08   728.2   718.6   788.9  747.24
     799   756.5   809.1  761.05   859.6  775.22   879.9   785.2   910.2  793.28
#Mann= 3 , 0 , 0
       0      .1       0   448.1    .045       0   462.4      .1       0
Bank Sta=448.1,462.4
XS Rating Curve= 0 ,0
Exp/Cntr=0.3,0.1

Type RM Length L Ch R = 1 ,1856.7  ,207.3,209,210.6
XS GIS Cut Line= 3
      1583108.57      296848.322     1582593.866      296877.273
     1582309.452      296921.881
#Sta/Elev= 30
       0  710.14    10.1  710.14    30.3  702.05    50.5  690.09   101.1  669.26
   121.3   656.3   161.7  639.25   181.9  636.17   242.6  634.47   306.2  619.77
   313.4   618.8   320.5  619.05   333.6  623.02   343.7  629.53   384.1  641.96
   414.4  643.64   444.8  648.81   495.3  649.63   525.4  655.92   545.3  662.55
   555.2  669.29     585  682.78   614.8  699.23   634.6   718.1   694.2  760.32
   704.1  771.96   714.1  781.04   763.7  811.13   783.6  827.37   803.4  838.35
#Mann= 3 , 0 , 0
       0      .1       0   306.2    .045       0   320.5      .1       0
Bank Sta=306.2,320.5
XS Rating Curve= 0 ,0
Exp/Cntr=0.3,0.1

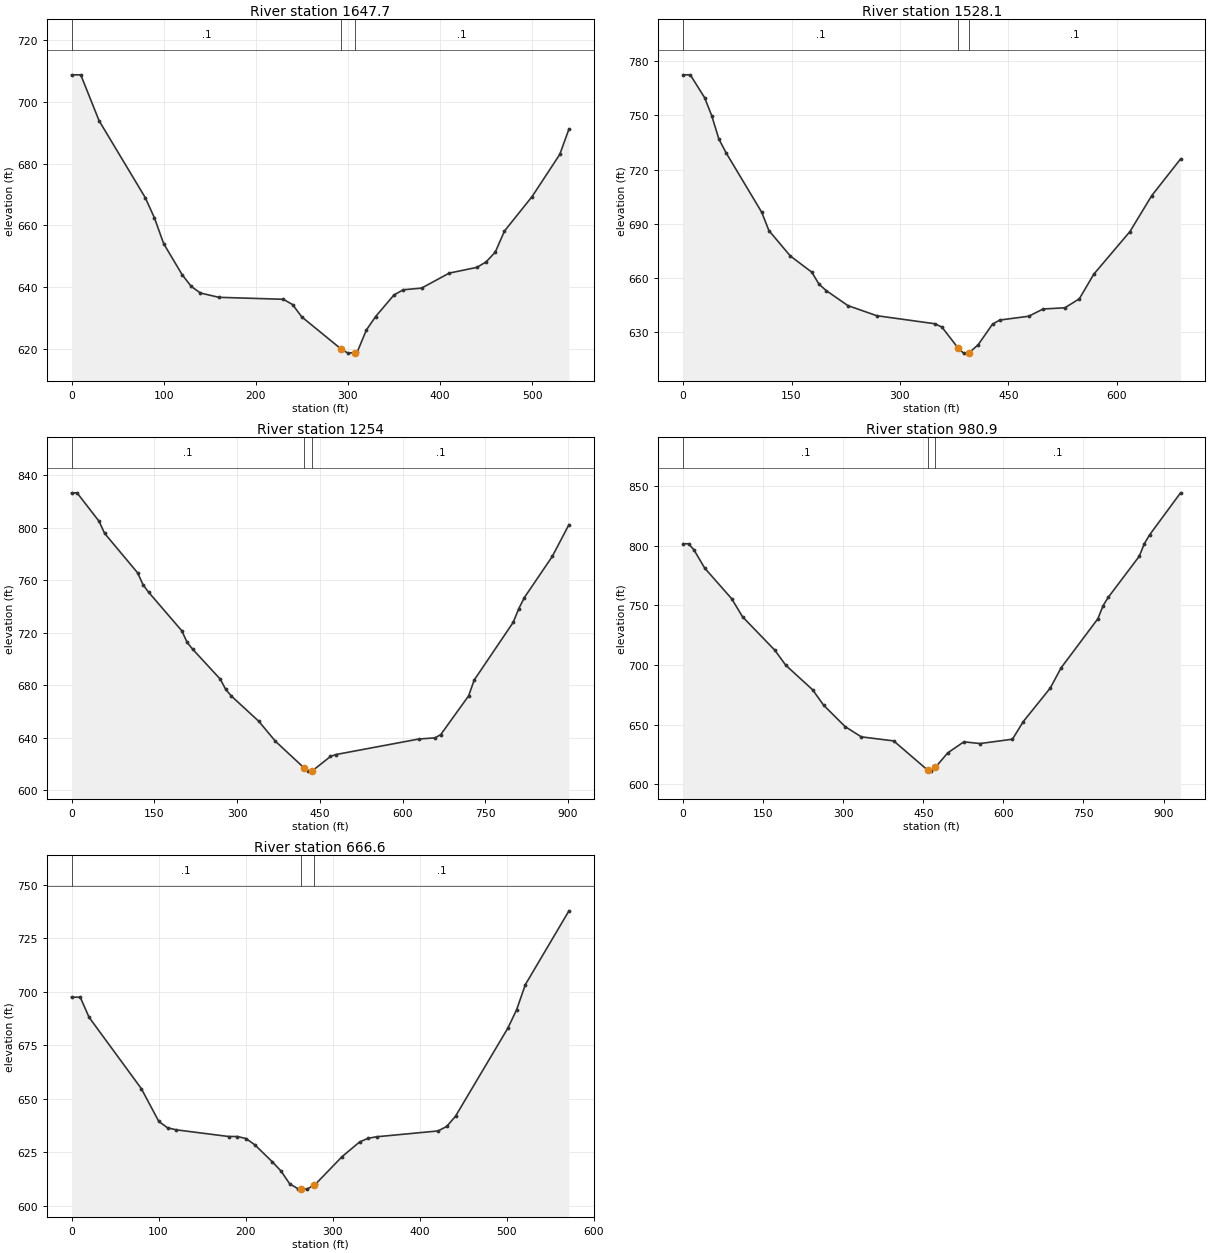
Type RM Length L Ch R = 1 ,1647.7  ,119.6,119.7,119.7
XS GIS Cut Line= 2
     1583068.306      296667.135     1582528.406      296652.494
#Sta/Elev= 30
       0  708.78      10  708.78      30  693.85      80  668.98      90  662.41
     100  654.06     120  644.01     130  640.16     140  638.02     160  636.63
     230  635.99     240  634.28     250  630.28   292.8  619.84   300.1  618.53
   307.3  618.73   310.1   618.8   320.1  626.01   330.1  630.37   350.1  637.39
   360.1  639.07   380.1  639.62   410.1  644.48   440.1  646.34   450.1   648.1
   460.1  651.29   470.1  658.13   500.1  669.32   530.1  682.96   540.1  691.21
#Mann= 3 , 0 , 0
       0      .1       0   292.8    .045       0   307.3      .1       0
Bank Sta=292.8,307.3
XS Rating Curve= 0 ,0
Exp/Cntr=0.3,0.1

Type RM Length L Ch R = 1 ,1528.1  ,274.6,274.1,273.5
XS GIS Cut Line= 3
     1583149.627      296540.522      1582961.73      296545.403
     1582461.484      296530.761
#Sta/Elev= 30
       0  772.57     9.9  772.57    29.7  759.92    39.6  749.85    49.5   736.9
    59.4  729.32   108.8  696.24   118.7  686.11   148.4  671.98   178.1     663
     188  656.37     198   652.8     228  644.45     268  638.84   348.1  634.39
   358.1  632.55   380.9  620.71   388.1  618.06   395.4  618.15   408.2  622.66
   428.2  634.14   438.2  636.43   478.2  638.53   498.2  642.56   528.3  643.23
   548.3  648.21   568.3  661.87   618.4  685.57   648.4  705.43   688.4  725.85
#Mann= 3 , 0 , 0
       0      .1       0   380.9    .045       0   395.4      .1       0
Bank Sta=380.9,395.4
XS Rating Curve= 0 ,0
Exp/Cntr=0.3,0.1

Type RM Length L Ch R = 1 ,1254    ,272.9,273.1,273.3
XS GIS Cut Line= 3
     1583283.839      296291.619      1582634.74      296286.739
     1582390.551      296222.187
#Sta/Elev= 30
       0  826.58      10  826.58    49.9   804.9    59.9  795.73   119.8   765.6
   129.8   756.4   139.8   750.8   199.7  721.52   209.7   712.5   219.7  707.34
   269.6  684.58   279.6   676.7   289.6  671.73   339.5  652.43   369.5  637.27
   422.1  616.71   429.4  614.46   436.7  614.77   469.4  625.64   479.3  627.11
   629.1   638.9   659.2  639.85   669.3  642.32   719.8  671.82   729.9  683.87
   800.7  727.93   810.8  738.36   820.9  746.77   871.4  778.06   901.7  802.36
#Mann= 3 , 0 , 0
       0      .1       0   422.1    .045       0   436.7      .1       0
Bank Sta=422.1,436.7
XS Rating Curve= 0 ,0
Exp/Cntr=0.3,0.1

Type RM Length L Ch R = 1 ,980.9   ,307.4,314.3,321.2
XS GIS Cut Line= 3
     1583299.731      296023.427     1582561.533      296010.993
      1582385.07      295931.724
#Sta/Elev= 30
       0  801.78    10.1  801.78    20.2  796.71    40.5  781.33      91  755.65
   111.3  740.53   171.9  712.44   192.2  699.93   242.7  679.26     263  666.49
   303.4  648.44   333.8  639.82   394.4  636.43   457.9     612   465.2  611.07
   472.6  614.27   495.6  626.34   525.9  635.65   556.3  634.21   616.9  637.85
   637.2  652.64   687.7  680.72     708  697.68     777  738.92   786.7  749.86
   796.3   756.8   854.4  791.27     864  801.88   873.7  809.17   931.8   844.5
#Mann= 3 , 0 , 0
       0      .1       0   457.9    .045       0   472.6      .1       0
Bank Sta=457.9,472.6
XS Rating Curve= 0 ,0
Exp/Cntr=0.3,0.1

Type RM Length L Ch R = 1 ,666.6   ,657.2,666.6,676
XS GIS Cut Line= 2
      1583183.79      295823.096     1582649.381      295620.557
#Sta/Elev= 30
       0  697.54      10  697.54    20.1  688.17    80.2  654.79   100.3  639.44
   110.3   636.5   120.3  635.54   180.5  632.42   190.5  632.42   200.5  631.46
   210.6  628.54   230.6  620.61   240.6  616.32   250.7  610.27   260.7   607.9
   263.3  607.88   270.7  607.82   278.1  609.66   280.7  610.31   310.8     623
   330.9  629.85   340.9  631.61   350.9  632.31   421.1  635.02   431.1  637.13
   441.2  641.93   501.3  683.08   511.3  691.61   521.4  703.42   571.5  737.91
#Mann= 3 , 0 , 0
       0      .1       0   263.3    .045       0   278.1      .1       0
Bank Sta=263.3,278.1
XS Rating Curve= 0 ,0
Exp/Cntr=0.3,0.1
Stream Node=bgbrnch         ,Main            , 0 , 0 ,Upstream end
Stream Node=bgbrnch         ,Main            , 0 , 1 ,Downstream end

Chan Stop Cuts=-1
Use User Specified Reach Order=0